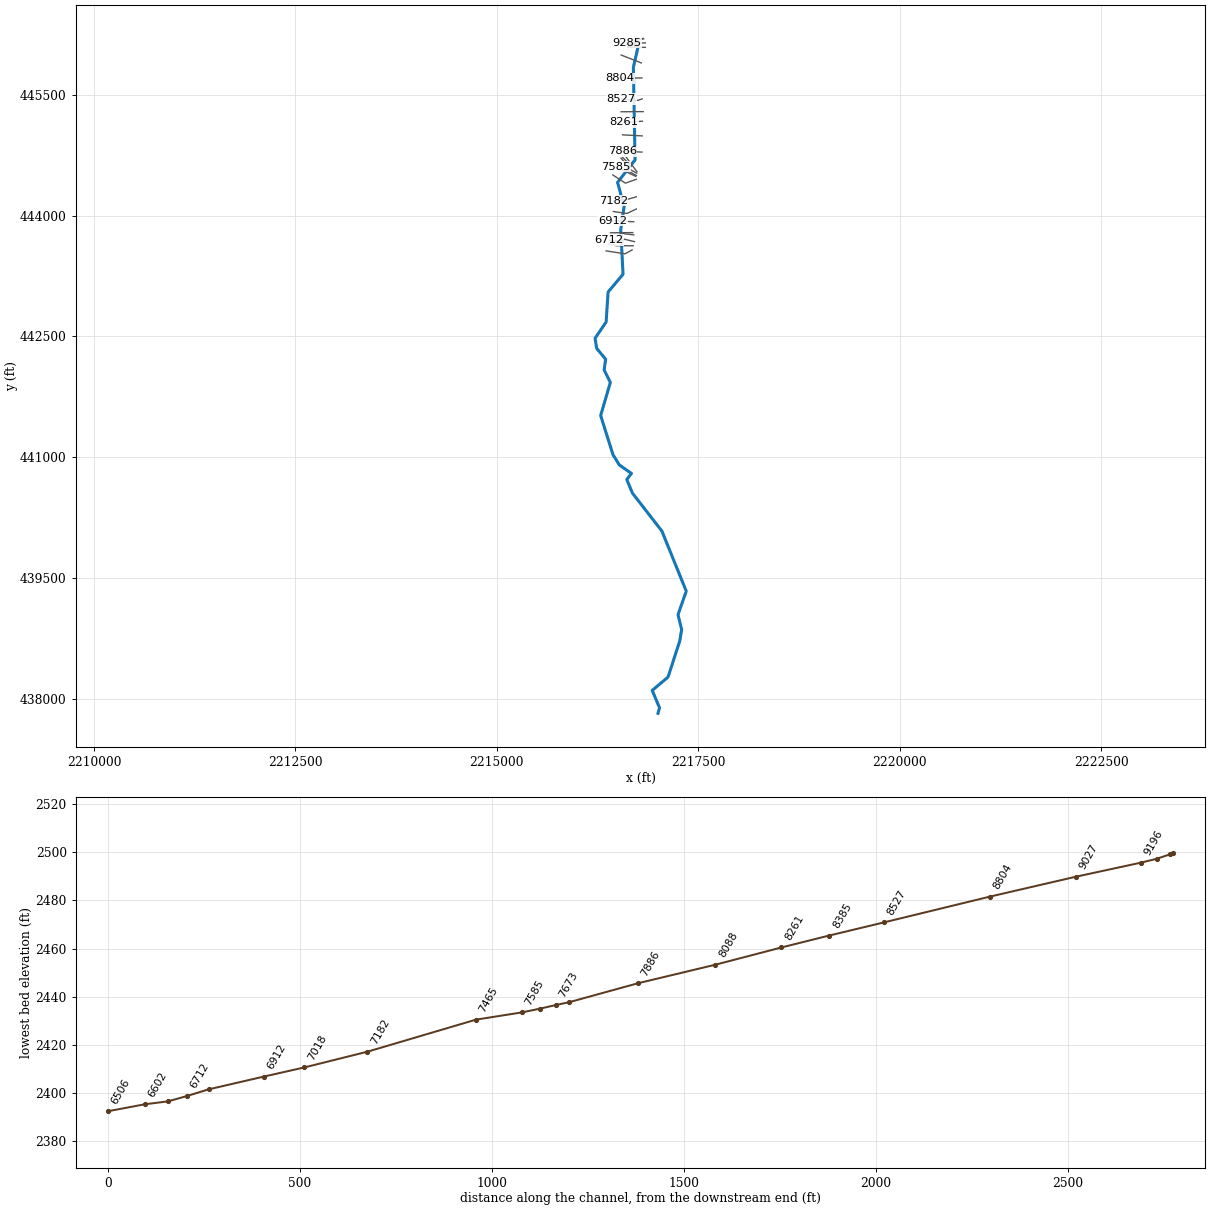
--- DRYCK.prj (project) ---

Proj Title=DRYCK
Current Plan=p01
Default Exp/Contr=0,0
English Units
Geom File=g01
Flow File=f01
Plan File=p01
Background Map Layer=Inundation Boundary (01pct Value_0)
BEGIN DESCRIPTION:
----------MODEL BY WOOD PLC 2021----------
Stream Name: Dry Creek I
Flood Zone: Enhanced Approximate
Pocahontas County, WV
HEC-RAS Version: RAS 6.1
Vertical Datum: NAVD88
Projection: NAD 1983 StatePlane West Virginia S FIPS 4702 (US Feet)
Terrain: 1-meter LIDAR (FEMA Region III 3DEP collected 2016-2018)
Land Use: 2019 NLCD
Hydrologic Method:
WV SIR2010-5033 regression equations
Model Notes:
Normal Depth tie in to Swago Creek
END DESCRIPTION:
DSS Export Rating Curves= 0
DSS Export Rating Curve Sorted= 0
DSS Export Volume Flow Curves= 0
DXF OffsetX= 0
DXF OffsetY= 0
DXF ScaleX= 0
DXF ScaleY= 0

--- DRYCK.p01 (plan) ---

Plan Title=Floodplain
Program Version=6.00
Short Identifier=Floodplain
Geom File=g01
Flow File=f01
Subcritical Flow
K Sum by GR= 0
Std Step Tol= 0.01
Critical Tol= 0.01
Num of Std Step Trials= 20
Max Error Tol= 0.3
Flow Tol Ratio= 0.001
Split Flow NTrial= 30
Split Flow Tol= 0.02
Split Flow Ratio= 0.02
Log Output Level= 0
Friction Slope Method= 1
Unsteady Friction Slope Method= 2
Unsteady Bridges Friction Slope Method= 1
Parabolic Critical Depth
Global Vel Dist= 0 , 0 , 0
Global Log Level= 0
CheckData=False
Encroach Param=-1 ,0,0, 0
Mapping Interval=1HOUR
Computation Time Step Use Courant=        0
Computation Time Step Use Time Series=    0
Computation Time Step Count To Double=0
Computation Time Step Max Doubling=0
Computation Time Step Max Halving=0
Computation Time Step Residence Courant=0
Run HTab= 0
Run UNet= 0
Run Sediment= 0
Run PostProcess= 0
Run WQNet= 0
Run RASMapper=-1
UNET Theta= 0
UNET Theta Warmup= 0
UNET ZTol= 0
UNET ZSATol= 0
UNET MxIter= 0
UNET Max Iter WO Improvement= 0
UNET MaxInSteps= 0
UNET DtIC= 0
UNET DtMin= 0
UNET MaxCRTS= 0
UNET WFStab= 0
UNET SFStab= 0
UNET WFX= 1
UNET SFX= 1
UNET Gravity=32.174
UNET 1D Methodology=Finite Difference
UNET DSS MLevel= 1
UNET Pardiso=0
UNET DZMax Abort= 0
UNET Use Existing IB Tables= 0
UNET Froude Reduction=False
UNET Froude Limit= 0
UNET Froude Power= 0
UNET D1 Cores= 0
UNET WindReference=Eulerian
UNET WindDragFormulation=Hsu (1988)
UNET D2 Coriolis=0
UNET D2 Cores= 0
UNET D2 Theta= 1
UNET D2 Theta Warmup= 1
UNET D2 Z Tol= 0.01
UNET D2 Volume Tol= 0.01
UNET D2 Max Iterations= 20
UNET D2 Equation= 0
UNET D2 RampUpFraction=0.1
UNET D2 TimeSlices= 1
UNET D2 Turbulence Formulation=Non-Conservative (original)
UNET D2 Eddy Viscosity=0.3
UNET D2 Transverse Eddy Viscosity=0.1
UNET D2 Smagorinsky Mixing=0
UNET D2 BCVolumeCheck=0
UNET D2 Cores=0
UNET D2 SolverType=PARDISO (Direct)
UNET D2 Minimum Iterations= 2147483647
UNET D2 Maximum Iterations= 2147483647
UNET D2 Restart Number= 10
UNET D2 Relaxation Coeff=1.3
UNET D2 SOR Precondition Iterations= 10
UNET D2 ILUT Maximum Fill= 8
UNET D2 ILUT Tolerance=1E-08
UNET D1D2 MaxIter= 0
UNET D1D2 ZTol=0.01
UNET D1D2 QTol=0.1
UNET D1D2 MinQTol=1
Write IC File= 0
Write IC File at Fixed DateTime=0
Write IC File at Sim End=0
Echo Input=False
Echo Parameters=False
Echo Output=False
Write Detailed= 0
HDF Write Warmup=0
HDF Write Time Slices=0
HDF Flush=0
HDF Compression= 1
HDF Chunk Size= 1
HDF Spatial Parts= 1
HDF Use Max Rows=0
HDF Fixed Rows= 1
Calibration Method= 0
Calibration Iterations= 20
Calibration Max Change=0.05
Calibration Tolerance=0.2
Calibration Maximum=1.5
Calibration Minimum=0.5
Calibration Optimization Method= 1
WQ AD Non Conservative
WQ ULTIMATE=-1
WQ Max Comp Step=1HOUR
WQ Output Interval=15MIN
WQ Output Selected Increments= 0
WQ Output face flow=0
WQ Output face velocity=0
WQ Output face area=0
WQ Output face dispersion=0
WQ Output cell volume=0
WQ Output cell surface area=0
WQ Output cell continuity=0
WQ Output cumulative cell continuity=0
WQ Output face conc=0
WQ Output face dconc_dx=0
WQ Output face courant=0
WQ Output face peclet=0
WQ Output face adv mass=0
WQ Output face disp mass=0
WQ Output cell mass=0
WQ Output cell source sink temp=0
WQ Output nsm pathways=0
WQ Output nsm derived pathways=0
WQ Create Restart=0
WQ Fixed Restart=0
WQ System Summary=0
WQ Write To DSS=0
Sorting and Armoring Iterations= 10
XS Update Threshold= 0.02
Bed Roughness Predictor= 0
Hydraulics Update Threshold= 0.02
Energy Slope Method= 1
Volume Change Method= 1
Sediment Retention Method= 0
Sediment TS Multiplier= 1
Warm Up Method= 0
XS Weighting Method= 0
Number of US Weighted Cross Sections= 1
Number of DS Weighted Cross Sections= 1
Upstream XS Weight=0
Main XS Weight=1
Downstream XS Weight=0
Number of DS XS's Weighted with US Boundary= 1
Upstream Boundary Weight= 1
Weight of XSs Associated with US Boundary= 0
Number of US XS's Weighted with DS Boundary= 1
Downstream Boundary Weight= 0.5
Weight of XSs Associated with DS Boundary= 0.5
Percentile Method= 0
Sediment Output Level= 3
Mass or Volume Output= 0
Output Increment Type= 1
Profile and TS Output Increment= 1
Transport Output Increment 1
XS Output Flag= 0
XS Output Increment= 10
Read HDF5 Sediment Hotstart= 0
Sediment Hotstart Type= 0
Write Gradation File= 0
Read Gradation Hotstart= 0
Write HDF5 File= 1
Write Binary Output= 1
Write DSS Sediment File= 0
DSS Sediment Output Type= 1
SV Curve= 0
Specific Gage Flag= 0
Subcell Erosion Methods= 0
Subcell Deposition Methods= 0
Advection Scheme= 1
Matrix Solver= 0
Implicit Weighting Factor= 1
Maximum Outer Loop Convergence Iterations= 5
Convergence Maximum Absolute= 0.001
Convergence RMSE= 0.0001
Grain Fractions Max Abs Error= 0.001
Max Subgrid Regions= 1
Max Subgrid Length Scale= 3.402823E+38
Initial Layer Thickness= 3.402823E+38
Min Layer Thickness= 3.402823E+38
Max Layer Thickness= 3.402823E+38
Number of Layers= 5

--- DRYCK.f01 (steady flow) ---

Flow Title=Flow
Program Version=6.10
Number of Profiles= 6
Profile Names=01pct,10pct,04pct,02pct,0_2pct,01plus
River Rch & RM=DRYCK,Main            ,9285
     755     403     534     641    1050    1120
River Rch & RM=DRYCK,Main            ,6015
     840     450     595     713    1160    1240
Boundary for River Rch & Prof#=DRYCK,Main            , 1
Up Type= 0
Dn Type= 3
Dn Slope=0.03599
Boundary for River Rch & Prof#=DRYCK,Main            , 2
Up Type= 0
Dn Type= 3
Dn Slope=0.03599
Boundary for River Rch & Prof#=DRYCK,Main            , 3
Up Type= 0
Dn Type= 3
Dn Slope=0.03599
Boundary for River Rch & Prof#=DRYCK,Main            , 4
Up Type= 0
Dn Type= 3
Dn Slope=0.03599
Boundary for River Rch & Prof#=DRYCK,Main            , 5
Up Type= 0
Dn Type= 3
Dn Slope=0.03599
Boundary for River Rch & Prof#=DRYCK,Main            , 6
Up Type= 0
Dn Type= 3
Dn Slope=0.03599
DSS Import GetInterval= 0
DSS Import GetPeak= 0
DSS Import FillOption= 0

--- DRYCK.g01 (geometry) ---

Geom Title=Geometry
Program Version=6.10

River Reach=DRYCK           ,Main
Reach XY= 30
     2216717.765      446171.1362216754.68681848446097.401352323
2216695.51368787445840.589965503     2216716.475      444691.531
2216499.54831227444412.1094851562216580.76343403444113.344348738
     2216538.326      443819.307     2216567.451      443271.273
2216381.57764983 443050.95957175 2216357.3887448442678.694070737
     2216220.097      442475.995     2216240.193      442350.919
     2216351.352      442215.943     2216332.812      442083.611
     2216409.705      441927.518     2216289.327      441517.723
2216442.64346146441030.581663777     2216521.582       440903.59
     2216671.787      440797.7812216613.68250787440722.581968596
2216683.78047772440553.699782793     2217049.539      440082.542
     2217352.004      439336.253      2217249.39      439044.127
     2217294.543      438860.399     2217271.854      438719.775
     2217126.045      438269.8192216929.44690125438104.153187437
     2217020.269      437888.025     2217001.413      437819.098

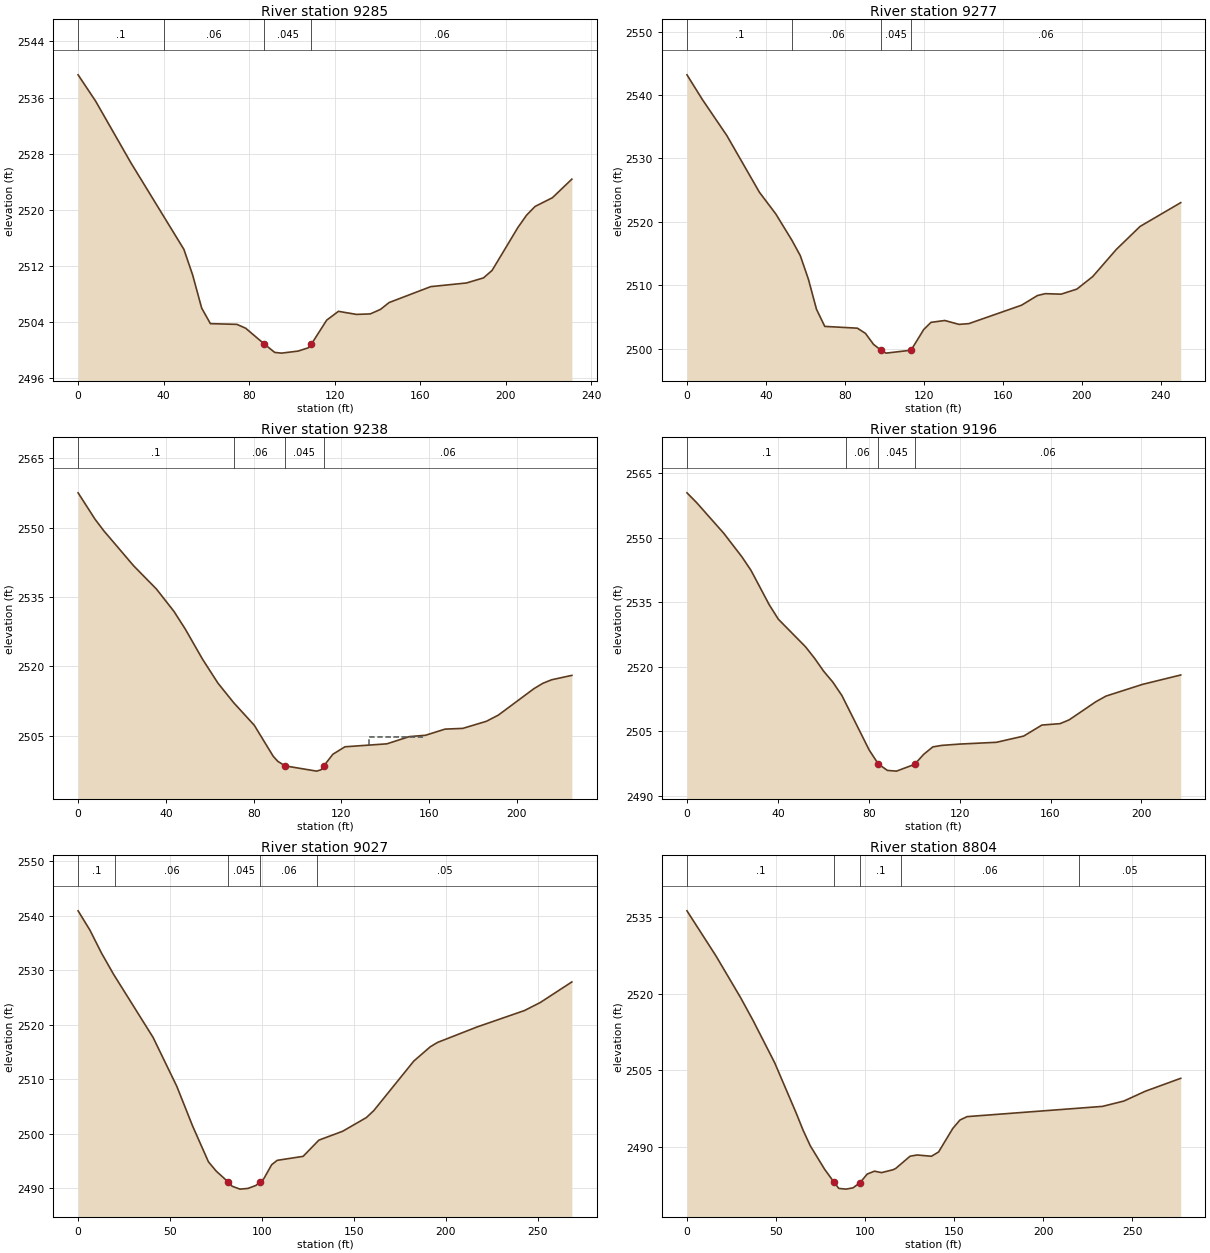
Type RM Length L Ch R = 1 ,9285    ,7.9,7.9,7.9
BEGIN DESCRIPTION:
structure xs 4
END DESCRIPTION:
XS GIS Cut Line= 5
 2216816.1185655 446200.382137832216731.74880628446178.683937942
2216711.39565383446159.692460866 2216704.9364091446138.947470246
2216611.08330045446148.219435211
#Sta/Elev= 30
       0 2539.24     8.2 2535.49    24.7  2526.7    49.5 2514.36    53.6  2510.7
    57.8    2506    61.9 2503.77    74.3 2503.67    78.4 2503.12    87.1 2500.87
      92 2499.67    95.2 2499.57   102.9 2499.86   107.7 2500.33  109.13 2500.85
   116.3 2504.27   121.8 2505.53   130.2 2505.09   136.7 2505.16   141.5 2505.81
   145.5 2506.78     165 2509.05   181.7 2509.57   189.7  2510.3   193.7 2511.37
   205.8  2517.5   209.8 2519.23   213.8 2520.48   221.9 2521.72     231 2524.37
#Mann= 4 ,-1,0
       0      .1       0      40     .06       0    87.1    .045       0
  109.13     .06       0
Bank Sta=87.1,109.13
XS Rating Curve= 0 ,0
Exp/Cntr(USF)=0,0
Exp/Cntr=0.5,0.3

Type RM Length L Ch R = 1 ,9277    ,35,35,35
BEGIN DESCRIPTION:
structure xs 3; 11.7 ft between structure and xs
END DESCRIPTION:
XS GIS Cut Line= 5
2216823.74505282446194.0530583642216731.85786051446170.456549782
2216713.90831137446148.0714197112216709.36754737446123.721759141
2216607.62167231 446126.11827093
#Sta/Elev= 30
       0 2543.21     7.8 2539.31    20.2 2533.62    36.7 2524.67      45 2521.24
    53.2 2517.07    57.4 2514.66    61.5 2510.95    65.6  2506.2    69.8 2503.49
    86.3 2503.21    90.4 2502.39    94.5 2500.65    98.4 2499.71   100.8 2499.27
   113.5 2499.73   119.9 2502.99   123.6 2504.13   130.6 2504.42   137.8 2503.81
   142.8 2503.93   169.5 2506.84   177.5 2508.36   181.5 2508.66   189.5 2508.58
   197.5 2509.38   205.5 2511.35   217.5 2515.65   229.5 2519.27   250.1 2523.03
#Mann= 4 ,-1,0
       0      .1       0    53.2     .06       0    98.4    .045       0
   113.5     .06       0
#XS Ineff= 2 , 0
            82.4  2502.5   127.2          2502.5
Permanent Ineff=
       F       F
Bank Sta=98.4,113.5
XS Rating Curve= 0 ,0
Exp/Cntr(USF)=0,0
Exp/Cntr=0.5,0.3

Type RM Length L Ch R = 1 ,9238    ,42.1,42.1,42.1
BEGIN DESCRIPTION:
structure xs 2; 10 ft between structure and xs
END DESCRIPTION:
XS GIS Cut Line= 4
2216843.84294391446143.3222698582216759.49372423446141.711514812
2216729.37077123446113.8531128962216631.17446751 446097.37323596
#Sta/Elev= 30
       0 2557.52     7.7 2551.83    11.7 2549.32    25.3 2541.75    35.7 2536.72
    43.7 2531.88    48.9 2528.02    56.7 2521.56    63.7  2516.4    70.9 2512.15
    80.3 2507.27    88.9 2500.58      91 2499.48    94.3  2498.5   108.7 2497.36
   110.7 2497.65  111.97 2498.49   116.1 2501.01   121.6 2502.62   140.7 2503.26
   150.9 2504.82   158.3 2505.11   167.2 2506.44   175.3  2506.6   186.1 2508.14
   191.5 2509.47   207.7 2515.18   211.8 2516.35   215.8 2517.11     225 2518.06
#Mann= 4 ,-1,0
       0      .1       0    70.9     .06       0    94.3    .045       0
  111.97     .06       0
#XS Ineff= 3 ,-1
       0      83  2501.2     121   132.7  2501.2   132.7   157.3 2504.68
Permanent Ineff=
       F       F       F
Bank Sta=94.3,111.97
XS Rating Curve= 0 ,0
Exp/Cntr(USF)=0,0
Exp/Cntr=0.5,0.3

Type RM Length L Ch R = 1 ,9196    ,169.5,169.5,169.5
BEGIN DESCRIPTION:
structure xs 1
END DESCRIPTION:
XS GIS Cut Line= 2
2216844.34378129446088.3066404742216627.06004571446089.638035913
#Sta/Elev= 30
       0 2560.48     4.2 2558.23    16.2 2551.06    24.2 2545.57    28.2 2542.42
    36.2 2534.44    40.2 2531.08    52.2 2524.64    56.2 2521.95    60.2 2518.94
    64.2 2516.43    68.2  2513.3    80.2 2500.63    84.2 2497.39    88.2 2495.89
    92.2 2495.72   100.2  2497.3   104.2 2499.64   108.2 2501.36   112.2 2501.71
   120.2 2502.02   136.2 2502.43   148.2 2503.88   156.2 2506.44   164.2 2506.77
   168.2 2507.65   179.9 2511.85   184.4 2513.18   200.5 2515.91   217.3 2518.09
#Mann= 4 ,-1,0
       0      .1       0      70     .06       0    84.2    .045       0
   100.2     .06       0
Bank Sta=84.2,100.2
XS Rating Curve= 0 ,0
Exp/Cntr(USF)=0,0
Exp/Cntr=0.3,0.1

Type RM Length L Ch R = 1 ,9027    ,222.8,222.8,222.8
XS GIS Cut Line= 2
2216794.11486129445894.654174565 2216544.2079022445993.008646087
#Sta/Elev= 30
       0 2540.91     6.4 2537.39    12.7 2533.18    19.3 2529.27    40.8 2517.69
    53.7 2508.72    62.3 2501.44    70.9 2494.88    75.2 2493.15   81.652491.186
    83.8  2490.4    88.1 2489.87    92.4    2490    96.7 2490.54    99.1 2491.21
     101 2491.77   105.3 2494.35   108.3 2495.15   122.4 2495.88     131 2498.86
   143.9 2500.48   156.8 2502.99   160.8 2504.25   182.6 2513.35   191.6 2515.98
   195.5 2516.77     217 2519.61   242.8 2522.62   251.4 2524.09   268.6 2527.87
#Mann= 5 ,-1,0
       0      .1       0      20     .06       0   81.65    .045       0
    99.1     .06       0     130     .05       0
Bank Sta=81.65,99.1
XS Rating Curve= 0 ,0
Exp/Cntr(USF)=0,0
Exp/Cntr=0.3,0.1

Type RM Length L Ch R = 1 ,8804    ,276.9,276.9,276.9
XS GIS Cut Line= 2
2216801.35438564445708.4399200012216524.22983695445706.584175255
#Sta/Elev= 30
       0 2536.26    16.3  2527.4    30.1 2519.22    37.2 2514.67    49.2 2506.46
    61.2 2496.65    65.2 2493.18    69.2 2490.15    77.2 2485.56    82.5 2483.01
    85.2 2481.78    89.2 2481.64    93.2 2481.89    97.2 2482.94   101.2 2484.61
   105.2 2485.16   109.2 2484.88   115.7 2485.45   117.2 2485.71   125.2  2488.1
   129.2 2488.34   137.2 2488.09   141.2 2488.93   149.2 2493.56   153.2  2495.2
   157.2 2495.87   233.2 2497.88   245.2 2498.93   257.2 2500.85   277.1 2503.39
#Mann= 5 ,-1,0
       0      .1       0    82.5    .045       0    97.2      .1       0
     120     .06       0     220     .05       0
Bank Sta=82.5,97.2
XS Rating Curve= 0 ,0
Exp/Cntr(USF)=0,0
Exp/Cntr=0.3,0.1

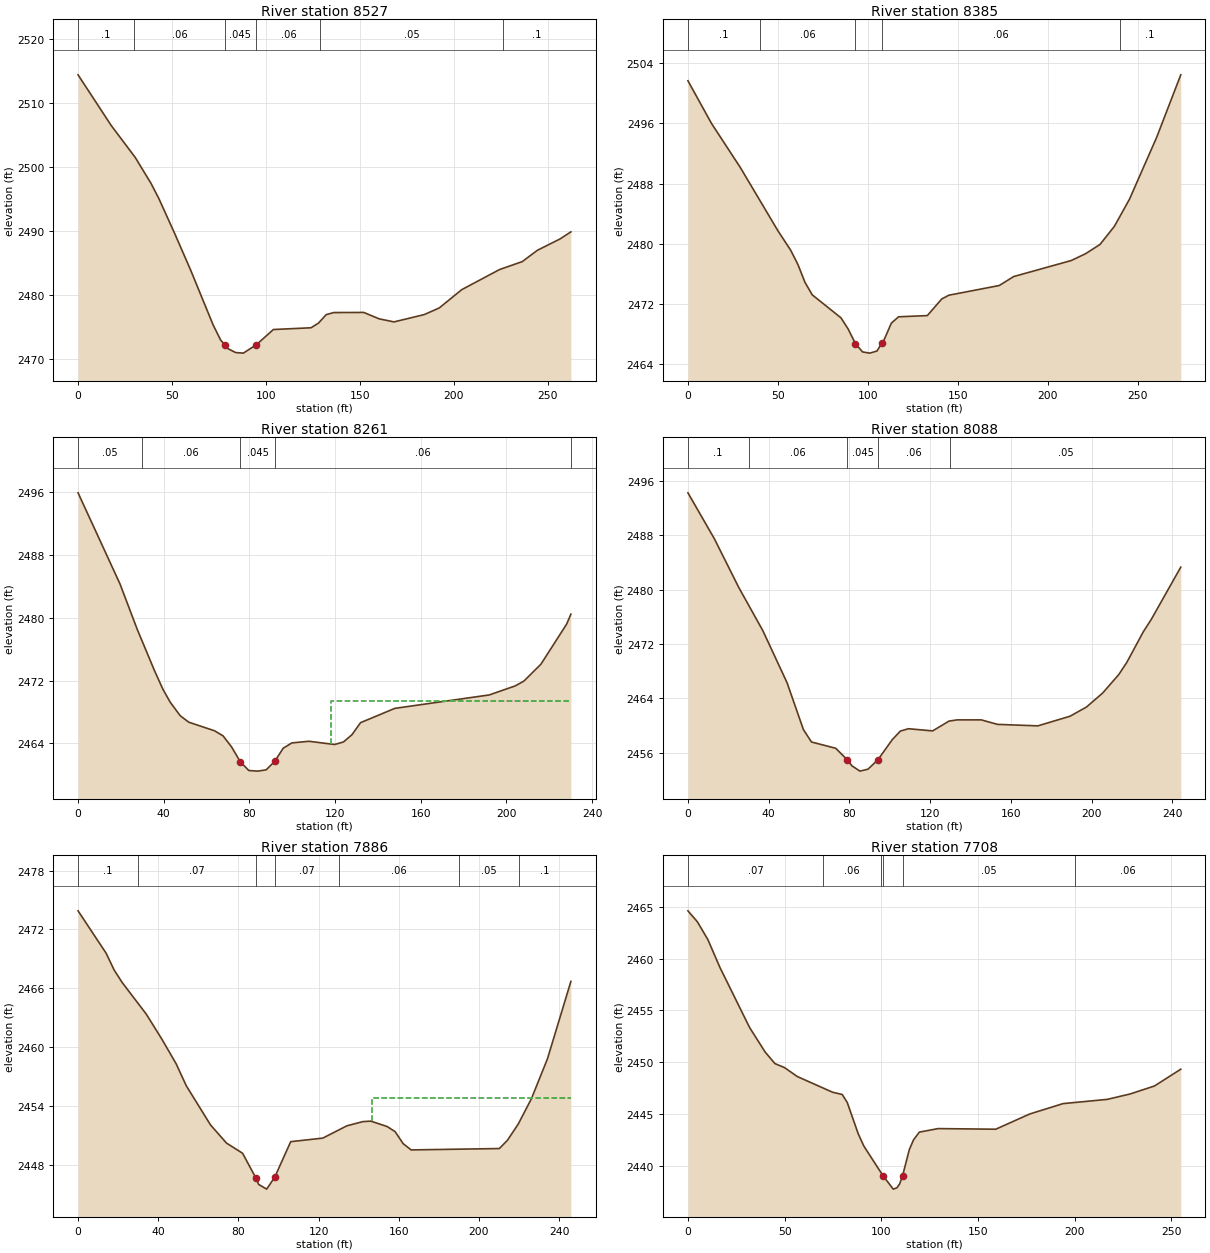
Type RM Length L Ch R = 1 ,8527    ,142,142,142
XS GIS Cut Line= 4
2216804.93117704445448.6382566522216749.02836076445429.671229702
2216662.17934262 445435.660817162216546.38065177445446.641727499
#Sta/Elev= 30
       0 2514.38    17.7 2506.44    30.4 2501.49    38.8 2497.44      43 2495.06
    51.5 2489.55    59.9  2483.9    71.9 2475.31    75.9 2472.94   77.992472.224
    79.9 2471.57    83.9 2470.98      88 2470.89    94.9 2472.19     104 2474.58
     124 2474.85     128 2475.58   132.1  2476.9   136.1 2477.23   152.1 2477.25
   160.3 2476.25   168.2 2475.77   184.3 2476.91   192.3 2477.95   204.3 2480.81
   224.4 2483.95   236.5 2485.19   244.5 2486.95   256.6 2488.73   262.4 2489.84
#Mann= 6 ,-1,0
       0      .1       0      30     .06       0   77.99    .045       0
    94.9     .06       0  129.03     .05       0  226.09      .1       0
Bank Sta=77.99,94.9
XS Rating Curve= 0 ,0
Exp/Cntr(USF)=0,0
Exp/Cntr=0.3,0.1

Type RM Length L Ch R = 1 ,8385    ,124.7,124.7,124.7
XS GIS Cut Line= 2
 2216817.2412784445290.4619518682216543.20963762445288.606207122
#Sta/Elev= 30
       0 2501.66    13.1 2495.99    29.1 2490.14      50 2481.73    57.1 2479.14
    61.1 2477.26    65.1 2474.85    69.1  2473.2    85.1 2470.14    89.1 2468.65
    93.1 2466.72    97.1 2465.61   101.1 2465.45   105.1 2465.73  107.982466.843
   109.1 2467.24   113.1 2469.44   117.1 2470.28   133.1 2470.44   141.1 2472.65
   145.1 2473.15   173.1 2474.44   181.1 2475.63   213.1 2477.76   221.1 2478.67
   229.1  2479.9   237.1 2482.31   245.5 2485.92   260.6 2494.14     274 2502.45
#Mann= 5 ,-1,0
       0      .1       0      40     .06       0    93.1    .045       0
  107.98     .06       0     240      .1       0
Bank Sta=93.1,107.98
XS Rating Curve= 0 ,0
Exp/Cntr(USF)=0,0
Exp/Cntr=0.3,0.1

Type RM Length L Ch R = 1 ,8261    ,172.1,172.1,172.1
XS GIS Cut Line= 2
2216807.72365609445171.532305324 2216578.2298892445155.449184195
#Sta/Elev= 30
       0 2495.91    19.6  2484.3    27.6 2478.55    35.6 2473.33    39.6 2470.91
      43 2469.27    47.7 2467.53    51.7 2466.71    63.7 2465.62    67.7 2464.97
    71.7 2463.55    75.7 2461.69    79.7 2460.56    83.8 2460.48    87.8 2460.64
    91.8 2461.72    95.8  2463.4    99.8 2464.07   107.8 2464.28   119.8 2463.87
   123.9 2464.19   127.9 2465.12   131.9 2466.65   147.9 2468.47     192 2470.18
     204 2471.32   208.1 2471.93   216.1 2474.09   228.1 2479.19   230.1 2480.46
#Mann= 5 ,-1,0
       0     .05       0      30     .06       0    75.7    .045       0
    91.8     .06       0     230     .05       0
#XS Ineff= 1 ,-1
  118.28230.0566 2469.41
Permanent Ineff=
       F
Bank Sta=75.7,91.8
XS Rating Curve= 0 ,0
Exp/Cntr(USF)=0,0
Exp/Cntr=0.3,0.1

Type RM Length L Ch R = 1 ,8088    ,202.3,202.3,202.3
XS GIS Cut Line= 2
2216805.24932976444989.0507386642216561.52818649445002.040951884
#Sta/Elev= 30
       0 2494.21    13.1 2487.46    25.1 2480.35    37.1 2473.96    49.1 2466.31
    57.2 2459.42    61.2  2457.6    73.2 2456.68   78.922454.988    81.2 2454.11
    85.2 2453.32    89.2 2453.61    94.1 2454.99   101.2 2457.94   105.2  2459.2
   109.2 2459.55   121.2 2459.23   129.3 2460.67   133.3 2460.85   145.3 2460.85
   153.3 2460.19   173.3 2459.97   189.3 2461.39   197.4 2462.74   205.4 2464.79
   213.4 2467.51   217.4 2469.31   225.5 2473.77   229.5 2475.62   244.1 2483.29
#Mann= 5 ,-1,0
       0      .1       0      30     .06       0   78.92    .045       0
    94.1     .06       0     130     .05       0
Bank Sta=78.92,94.1
XS Rating Curve= 0 ,0
Exp/Cntr(USF)=0,0
Exp/Cntr=0.3,0.1

Type RM Length L Ch R = 1 ,7886    ,178.1,178.1,178.1
XS GIS Cut Line= 2
2216802.15642185444788.0117245472216556.57953384444799.764774603
#Sta/Elev= 30
       0  2473.9      14 2469.59      18 2467.88      22 2466.61      34  2463.4
      42 2460.78    48.9 2458.35      54  2456.1    66.1 2452.11    74.1 2450.26
    82.1 2449.23   88.612446.754    90.1 2446.06    94.1 2445.58    98.1 2446.78
   106.1 2450.41   122.1 2450.77   134.1 2452.02   142.1 2452.45   146.1  2452.5
   154.2 2451.95   158.2 2451.43   162.2 2450.21   166.2 2449.57   210.2 2449.71
   214.2 2450.54   219.6 2452.19   226.2 2454.78   234.2 2458.84   245.9 2466.72
#Mann= 7 ,-1,0
       0      .1       0      30     .07       0   88.61    .045       0
    98.1     .07       0     130     .06       0     190     .05       0
     220      .1       0
#XS Ineff= 1 ,-1
  146.62 245.858 2454.89
Permanent Ineff=
       F
Bank Sta=88.61,98.1
XS Rating Curve= 0 ,0
Exp/Cntr(USF)=0,0
Exp/Cntr=0.3,0.1

Type RM Length L Ch R = 1 ,7708    ,34.8,34.8,34.8
BEGIN DESCRIPTION:
structure xs 4
END DESCRIPTION:
XS GIS Cut Line= 2
 2216739.0611005 444544.909162862216588.12719451444750.278248051
#Sta/Elev= 30
       0 2464.61     4.9 2463.55    10.3 2461.84    16.6 2459.13    31.9 2453.35
      40 2450.97      45 2449.87      50 2449.48    56.6 2448.62    74.8 2447.11
    79.8 2446.89    82.4 2446.12    88.1 2443.09      91 2441.91     1012439.023
   106.2 2437.76   108.1 2437.89   109.5 2438.26     111 2439.03   114.5 2441.57
   116.7 2442.52   119.7 2443.26   129.4  2443.6   159.2 2443.54   176.8 2445.01
     194 2446.01   216.9 2446.42   228.7 2446.94   241.3 2447.71   254.9 2449.33
#Mann= 6 ,-1,0
       0     .07       0      70     .06       0     100     .05       0
     101    .045       0     111     .05       0     200     .06       0
Bank Sta=101,111
XS Rating Curve= 0 ,0
Exp/Cntr(USF)=0,0
Exp/Cntr=0.5,0.3

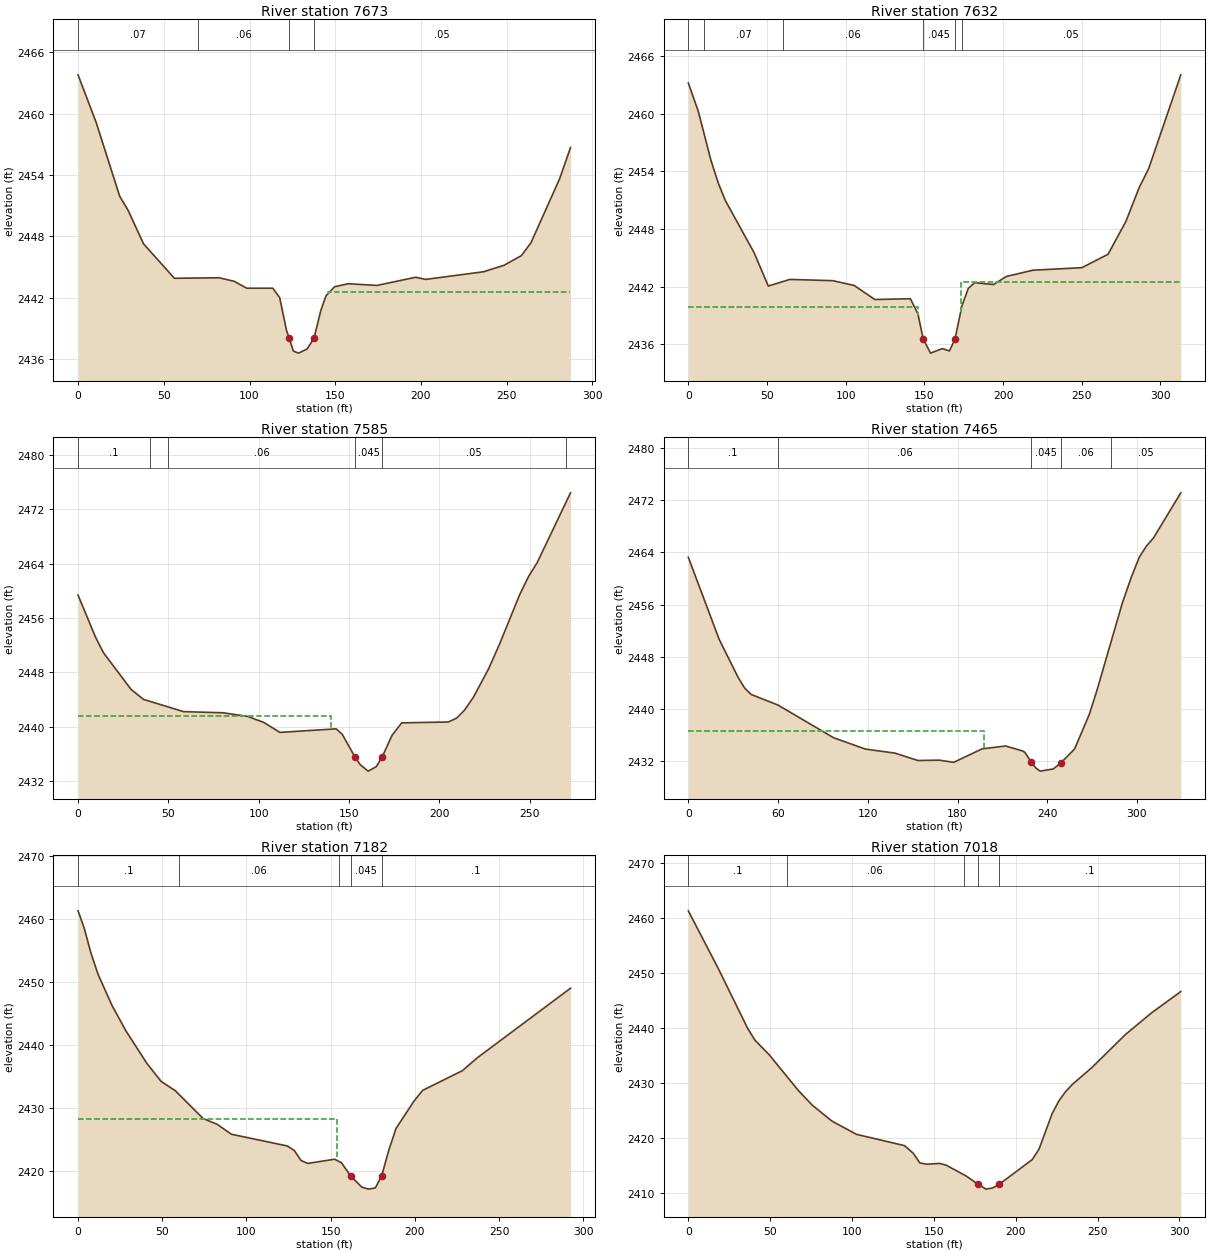
Type RM Length L Ch R = 1 ,7673    ,40.8,40.8,40.8
BEGIN DESCRIPTION:
structure xs 3; 7.9 ft between structure and xs
END DESCRIPTION:
XS GIS Cut Line= 4
2216737.49470598444526.8761096662216651.08675036444574.040197549
2216651.22251587444634.6034922362216559.67244175444724.297821611
#Sta/Elev= 30
       0 2463.79    10.6 2459.12    24.3 2451.91    29.2 2450.54    38.2 2447.26
    56.2 2443.89    82.3 2443.94    91.1 2443.59    98.4 2442.92   113.6 2442.92
   117.6    2442   121.6 2438.78  123.112438.047   125.6 2436.77   128.6 2436.57
   133.6 2436.98   137.6 2438.02   141.6 2440.75   144.6 2442.17   149.6 2443.06
   157.6 2443.36   174.3 2443.19   196.9 2443.99   202.7 2443.78   236.5 2444.53
   248.4 2445.16   258.5  2446.1   264.1 2447.35   280.9 2453.64   287.2 2456.68
#Mann= 4 ,-1,0
       0     .07       0      70     .06       0  123.11    .045       0
   137.6     .05       0
#XS Ineff= 2 ,-1
       0     115 2440.98   145.5287.1711  2442.5
Permanent Ineff=
       F       F
Bank Sta=123.11,137.6
XS Rating Curve= 0 ,0
Exp/Cntr(USF)=0,0
Exp/Cntr=0.5,0.3

Type RM Length L Ch R = 1 ,7632    ,47.3,47.3,47.3
BEGIN DESCRIPTION:
structure xs 2; 10.9 ft between structure and xs
END DESCRIPTION:
XS GIS Cut Line= 4
2216732.87528468444497.2783810542216615.34478412 444560.99228399
 2216615.9633657444628.4176764172216542.35215745444712.544771555
#Sta/Elev= 30
       0 2463.19     6.3 2460.26    14.4 2455.13      19 2452.79    23.5 2450.97
    41.8 2445.53    50.8 2442.06    64.5 2442.75    91.8 2442.62   105.4 2442.12
   118.5 2440.66   141.1 2440.74   145.9 2439.16   149.2 2436.57   153.9 2435.08
   161.3 2435.55   165.9 2435.31   169.4 2436.52   173.9 2440.03   177.9 2441.82
   181.9 2442.41   193.9 2442.22   202.1 2443.06     219 2443.71     250 2443.97
   266.7 2445.37     278 2448.78   286.5 2452.32   292.5 2454.28   312.9 2464.04
#Mann= 6 ,-1,0
       0      .1       0      10     .07       0      60     .06       0
   149.2    .045       0   169.4     .06       0  173.69     .05       0
#XS Ineff= 2 , 0
             146  2439.9     173          2442.5
Permanent Ineff=
       F       F
Bank Sta=149.2,169.4
XS Rating Curve= 0 ,0
Exp/Cntr(USF)=0,0
Exp/Cntr=0.5,0.3

Type RM Length L Ch R = 1 ,7585    ,120.1,120.1,120.1
BEGIN DESCRIPTION:
structure xs 1
END DESCRIPTION:
XS GIS Cut Line= 2
2216724.83372411444486.762494162 2216479.2568361444604.911576304
#Sta/Elev= 30
       0 2459.37     9.6 2453.24      14 2450.93    29.3 2445.53    36.2 2444.05
    58.4 2442.25    80.2 2442.08    93.9 2441.55   102.8 2440.66   111.7  2439.2
   142.8 2439.72   146.2 2438.92   153.2 2435.61   156.1 2434.47   160.5 2433.51
     165 2434.16  168.312435.607   173.8 2438.79   179.1  2440.6   204.9 2440.73
   209.4 2441.28   213.8 2442.45   218.7 2444.33   227.1 2448.49   233.1 2452.08
   244.3 2459.38   249.3  2462.1   254.1 2464.16     270    2473   272.5 2474.39
#Mann= 6 ,-1,0
       0      .1       0      40     .07       0      50     .06       0
   153.2    .045       0  168.31     .05       0     270      .1       0
#XS Ineff= 2 , 0
          139.94 2441.63
Permanent Ineff=
       F       F
Bank Sta=153.2,168.31
XS Rating Curve= 0 ,0
Exp/Cntr(USF)=0,0
Exp/Cntr=0.3,0.1

Type RM Length L Ch R = 1 ,7465    ,282.8,282.8,282.8
XS GIS Cut Line= 3
2216731.58668124444450.4897887372216597.07849585444402.255842759
2216440.82358514444503.941742751
#Sta/Elev= 30
       0 2463.26    20.6  2450.7    33.4 2444.81    37.6 2443.25    41.9 2442.25
      60 2440.61    97.1 2435.61   118.4 2433.87   138.2 2433.25   153.5 2432.12
   167.8 2432.17   177.5 2431.84   196.5 2433.91   212.2 2434.34   223.7 2433.57
   225.1 2433.35229.26662431.887   232.4 2430.96   235.3 2430.49     244 2430.82
248.96572431.712   258.3 2433.89   268.1 2439.17   272.9 2442.61   290.2 2456.24
     296 2460.07   301.5 2463.26   306.2 2464.94     311 2466.21   329.3 2473.14
#Mann= 5 ,-1,0
       0      .1       0      60     .06       0229.2666    .045       0
248.9657     .06       0  282.89     .05       0
#XS Ineff= 2 , 0
          197.58 2436.71
Permanent Ineff=
       F       F
Bank Sta=229.2666,248.9657
XS Rating Curve= 0 ,0
Exp/Cntr(USF)=0,0
Exp/Cntr=0.3,0.1

Type RM Length L Ch R = 1 ,7182    ,164.4,164.4,164.4
XS GIS Cut Line= 3
2216731.58668124444232.8400117332216611.32052888444198.045134716
 2216444.7034864444184.496538884
#Sta/Elev= 30
       0 2461.36     3.6 2458.68     7.7 2454.62    11.9 2451.27    20.2 2446.32
    28.5 2442.27      41 2437.09    49.4 2434.26    57.7 2432.81    74.3 2428.38
    82.7 2427.45      91 2425.89   124.3 2424.02   128.4 2423.31   132.4 2421.72
   136.4 2421.25   152.4 2421.92   156.4 2421.36161.92212419.244   168.5 2417.49
   172.5 2417.17   176.5 2417.36180.2141 2419.21   184.5 2423.34   188.8  2426.8
   199.4 2431.12   204.6 2432.85   228.2 2435.98   236.9 2437.99   292.4 2449.07
#Mann= 5 ,-1,0
       0      .1       0      60     .06       0   155.2      .1       0
161.9221    .045       0180.2141      .1       0
#XS Ineff= 2 , 0
           153.8 2428.34
Permanent Ineff=
       F       F
Bank Sta=161.9221,180.2141
XS Rating Curve= 0 ,0
Exp/Cntr(USF)=0,0
Exp/Cntr=0.3,0.1

Type RM Length L Ch R = 1 ,7018    ,105.7,105.7,105.7
XS GIS Cut Line= 3
2216732.70010535444081.8019356382216617.12656508444025.985169029
2216446.39292604  444050.2818792
#Sta/Elev= 30
       0 2461.32    18.4 2450.75    36.1 2439.99    40.6 2437.79    49.4  2435.1
    67.2 2428.59    75.7 2425.92    87.7 2423.02   102.7  2420.6     132 2418.55
   137.4 2417.15   141.4  2415.4   145.5 2415.16   153.5  2415.3   157.6 2414.97
   169.7 2413.01  176.95 2411.53   181.8 2410.62   185.9 2410.83   189.9  2411.5
   210.1 2416.01   214.2  2417.9   222.2 2424.36   226.3 2426.68   230.3 2428.33
   234.6 2429.71   246.5 2432.77     267 2438.79   282.8  2442.7   300.8 2446.61
#Mann= 5 ,-1,0
       0      .1       0      60     .06       0  168.35      .1       0
  176.95    .045       0   189.9      .1       0
Bank Sta=176.95,189.9
XS Rating Curve= 0 ,0
Exp/Cntr(USF)=0,0
Exp/Cntr=0.3,0.1

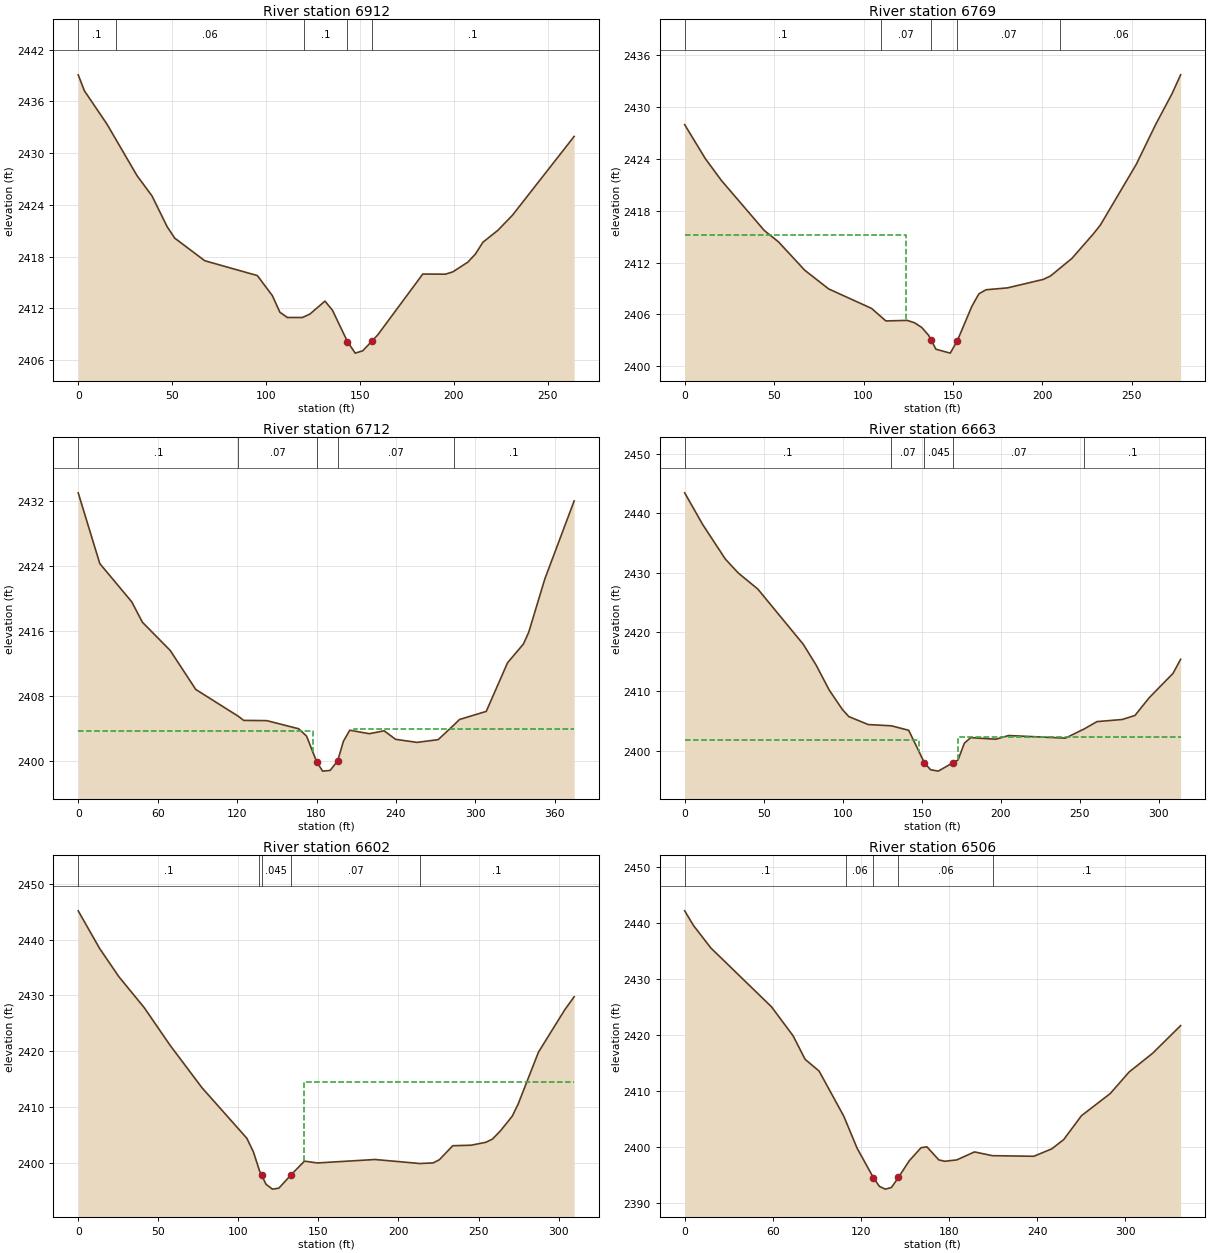
Type RM Length L Ch R = 1 ,6912    ,143.4,143.4,143.4
XS GIS Cut Line= 2
2216699.48366924443923.2498539412216435.65038346443934.889557725
#Sta/Elev= 30
       0 2439.07     3.3 2437.22    15.3 2433.36    31.3 2427.39    39.3 2425.03
    47.4 2421.45    51.4 2420.14    67.4 2417.52    95.4  2415.8   103.4 2413.47
   107.4 2411.55   111.4 2410.94   119.4 2410.94   123.4 2411.34   131.4 2412.84
   135.4 2411.78   143.4 2408.14   147.5 2406.81   151.5 2407.08   156.4  2408.2
   159.5 2408.92   183.5 2415.98   195.5 2415.96   199.5 2416.23   207.5 2417.36
   211.5 2418.29   215.5 2419.66   223.5 2421.05   231.3 2422.81   264.1 2431.93
#Mann= 5 ,-1,0
       0      .1       0      20     .06       0     120      .1       0
   143.4    .045       0   156.4      .1       0
Bank Sta=143.4,156.4
XS Rating Curve= 0 ,0
Exp/Cntr(USF)=0,0
Exp/Cntr=0.3,0.1

Type RM Length L Ch R = 1 ,6769    ,56.4,56.4,56.4
BEGIN DESCRIPTION:
structure xs 4
END DESCRIPTION:
XS GIS Cut Line= 2
2216688.62622718443788.3251903642216411.37796217443786.098296669
#Sta/Elev= 30
       0 2427.99    11.5 2424.07    20.5 2421.53    44.5 2415.73    52.5  2414.4
    67.1 2411.13    80.5 2408.96   104.5  2406.7   112.5 2405.25   124.5 2405.31
   128.5 2405.04   132.5  2404.5   136.5 2403.56  137.822403.018   140.5 2401.97
   148.5 2401.52   152.5 2402.98   160.5 2406.91   164.5 2408.39   168.5 2408.86
   180.5 2409.08   200.5 2410.06   204.5 2410.45   216.5 2412.49   228.5 2415.33
   232.5 2416.38   252.5 2423.39   263.4 2428.03   272.5 2431.57   277.3 2433.76
#Mann= 5 ,-1,0
       0      .1       0     110     .07       0  137.82    .045       0
   152.5     .07       0     210     .06       0
#XS Ineff= 2 , 0
          123.96 2415.18
Permanent Ineff=
       F       F
Bank Sta=137.82,152.5
XS Rating Curve= 0 ,0
Exp/Cntr(USF)=0,0
Exp/Cntr=0.5,0.3

Type RM Length L Ch R = 1 ,6712    ,49.5,49.5,49.5
BEGIN DESCRIPTION:
structure xs 3; 12.6 ft between structure and xs
END DESCRIPTION:
XS GIS Cut Line= 6
2216700.31741907443759.9322957552216562.43601454443776.633998466
2216559.08646102443743.2164333532216539.92744723443718.403940076
2216525.09113231443682.2915845682216394.11953603443696.465825452
#Sta/Elev= 30
       0 2433.03    16.3 2424.32    40.4 2419.61    48.5 2417.09    69.5 2413.61
    88.8 2408.81     121  2405.5     125    2405   142.4 2404.97   166.5 2403.97
   172.5 2403.06   180.1 2399.91   184.6 2398.75   190.3 2398.84     196 2400.02
   200.3 2402.42   205.1 2403.79   219.9 2403.36   231.1 2403.72   239.7 2402.67
   255.9 2402.29   271.9 2402.63     284 2404.47     288 2405.11   308.2 2406.11
   324.3  2412.1   336.3 2414.41   340.3 2415.86   352.4  2422.4   374.6 2432.03
#Mann= 5 ,-1,0
       0      .1       0     121     .07       0   180.1    .045       0
     196     .07       0     284      .1       0
#XS Ineff= 2 , 0
       0   177.5  2403.7   208.6       0    2404
Permanent Ineff=
       F       F
Bank Sta=180.1,196
XS Rating Curve= 0 ,0
Exp/Cntr(USF)=0,0
Exp/Cntr=0.5,0.3

Type RM Length L Ch R = 1 ,6663    ,61.1,61.1,61.1
BEGIN DESCRIPTION:
structure xs 2; 9.3 ft between structure and xs
END DESCRIPTION:
XS GIS Cut Line= 4
2216709.15226267443676.339778214  2216577.552502443708.117426207
2216564.42585831 443673.17610423 2216423.3697222443678.830568521
#Sta/Elev= 30
       0 2443.44    11.4  2438.1    25.7 2432.29    33.9 2429.93    46.3 2427.22
    75.1  2417.9    83.3 2414.36    91.5 2410.19    99.8 2406.93   103.9 2405.72
   116.2 2404.38   130.8 2404.17   141.8 2403.41   151.7 2397.96   155.6 2396.77
   160.5 2396.53169.52972397.905     173  2398.4     177 2401.23     181 2402.17
     197 2401.91     205 2402.53     241 2402.09     253 2403.66     261 2404.88
   276.9 2405.23     285 2405.91   293.9 2408.87   309.1 2413.01   313.9 2415.38
#Mann= 5 ,-1,0
       0      .1       0   130.8     .07       0   151.7    .045       0
169.5297     .07       0     253      .1       0
#XS Ineff= 2 , 0
       0   148.4  2401.7   172.8       0  2402.2
Permanent Ineff=
       F       F
Bank Sta=151.7,169.5297
XS Rating Curve= 0 ,0
Exp/Cntr(USF)=0,0
Exp/Cntr=0.5,0.3

Type RM Length L Ch R = 1 ,6602    ,95.5,95.5,95.5
BEGIN DESCRIPTION:
structure xs 1
END DESCRIPTION:
XS GIS Cut Line= 3
2216693.46268781443624.6429849672216483.50249902443625.790757223
2216386.43631666443648.915700452
#Sta/Elev= 30
       0 2445.17    13.3 2438.46    25.3  2433.4    41.3 2427.79    57.3  2421.1
    77.3 2413.46   105.3 2404.41   109.4 2401.97   113.2 2398.59  114.472397.827
   117.3 2396.15   121.3 2395.29   125.3 2395.46   133.1 2397.91   141.3 2400.31
   149.3 2399.98   185.3  2400.6   213.4 2399.88   221.6 2399.99   225.5 2400.55
   233.9 2403.07   245.4 2403.16   254.5 2403.68   258.7 2404.26   263.9 2405.81
     271 2408.35   274.7 2410.51   287.4 2419.83   303.8 2427.42   309.7 2429.77
#Mann= 5 ,-1,0
       0      .1       0   113.2     .07       0  114.47    .045       0
   133.1     .07       0   213.4      .1       0
#XS Ineff= 2 , 0
       0                   141.1       0 2414.49
Permanent Ineff=
       F       F
Bank Sta=114.47,133.1
XS Rating Curve= 0 ,0
Exp/Cntr(USF)=0,0
Exp/Cntr=0.3,0.1

Type RM Length L Ch R = 1 ,6506    ,123.3,123.3,123.3
XS GIS Cut Line= 3
 2216680.1278612443573.3916398122216592.65970458443525.520554097
2216357.44128341 443560.98061759
#Sta/Elev= 30
       0 2442.15       6 2439.53    17.8 2435.52    59.1    2425    73.8 2419.82
      82 2415.61    91.5 2413.52   108.3 2405.46   117.4 2399.72   128.5 2394.46
   132.6  2392.9   136.6 2392.42   140.7  2392.7   145.5  2394.5   152.8 2397.46
   160.9 2399.82   164.9 2399.98     173 2397.64   177.1  2397.4   185.2 2397.64
   197.3 2399.07   209.4  2398.4   237.7 2398.29   249.9 2399.62     258 2401.27
   270.1 2405.54   289.7  2409.5   302.5 2413.34   318.6 2416.71   337.6 2421.64
#Mann= 5 ,-1,0
       0      .1       0  109.71     .06       0   128.5    .045       0
   145.5     .06       0  209.71      .1       0
Bank Sta=128.5,145.5
XS Rating Curve= 0 ,0
Exp/Cntr(USF)=0,0
Exp/Cntr=0.3,0.1