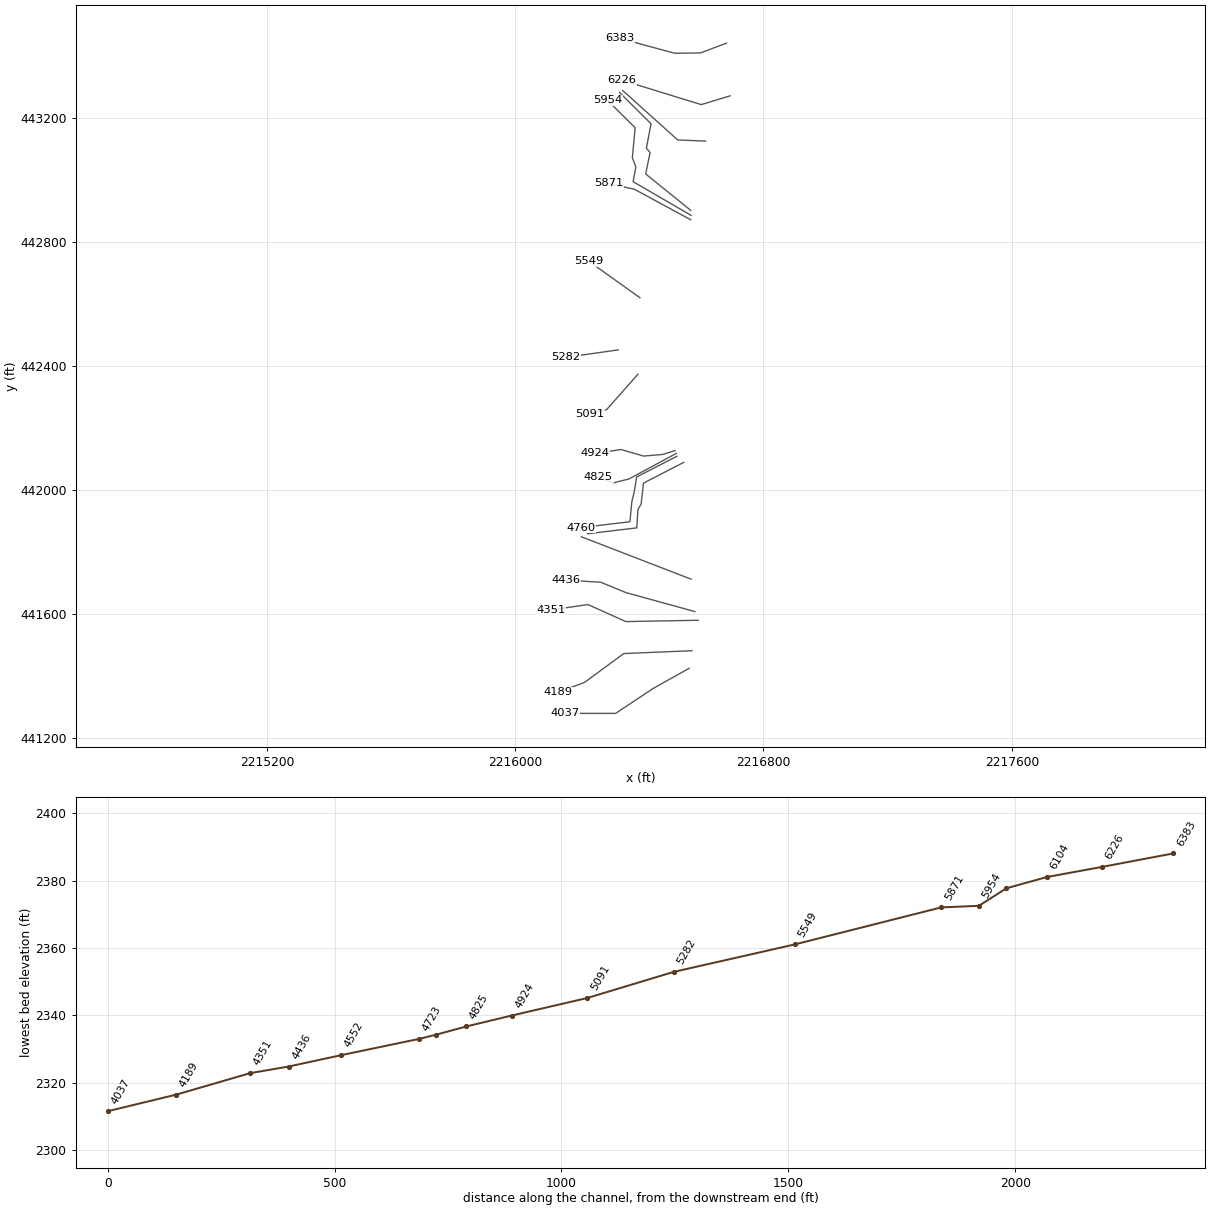
HEC-RAS study DRYCK.prj: DRYCK

--- DRYCK.g01 (geometry) --- (continued)

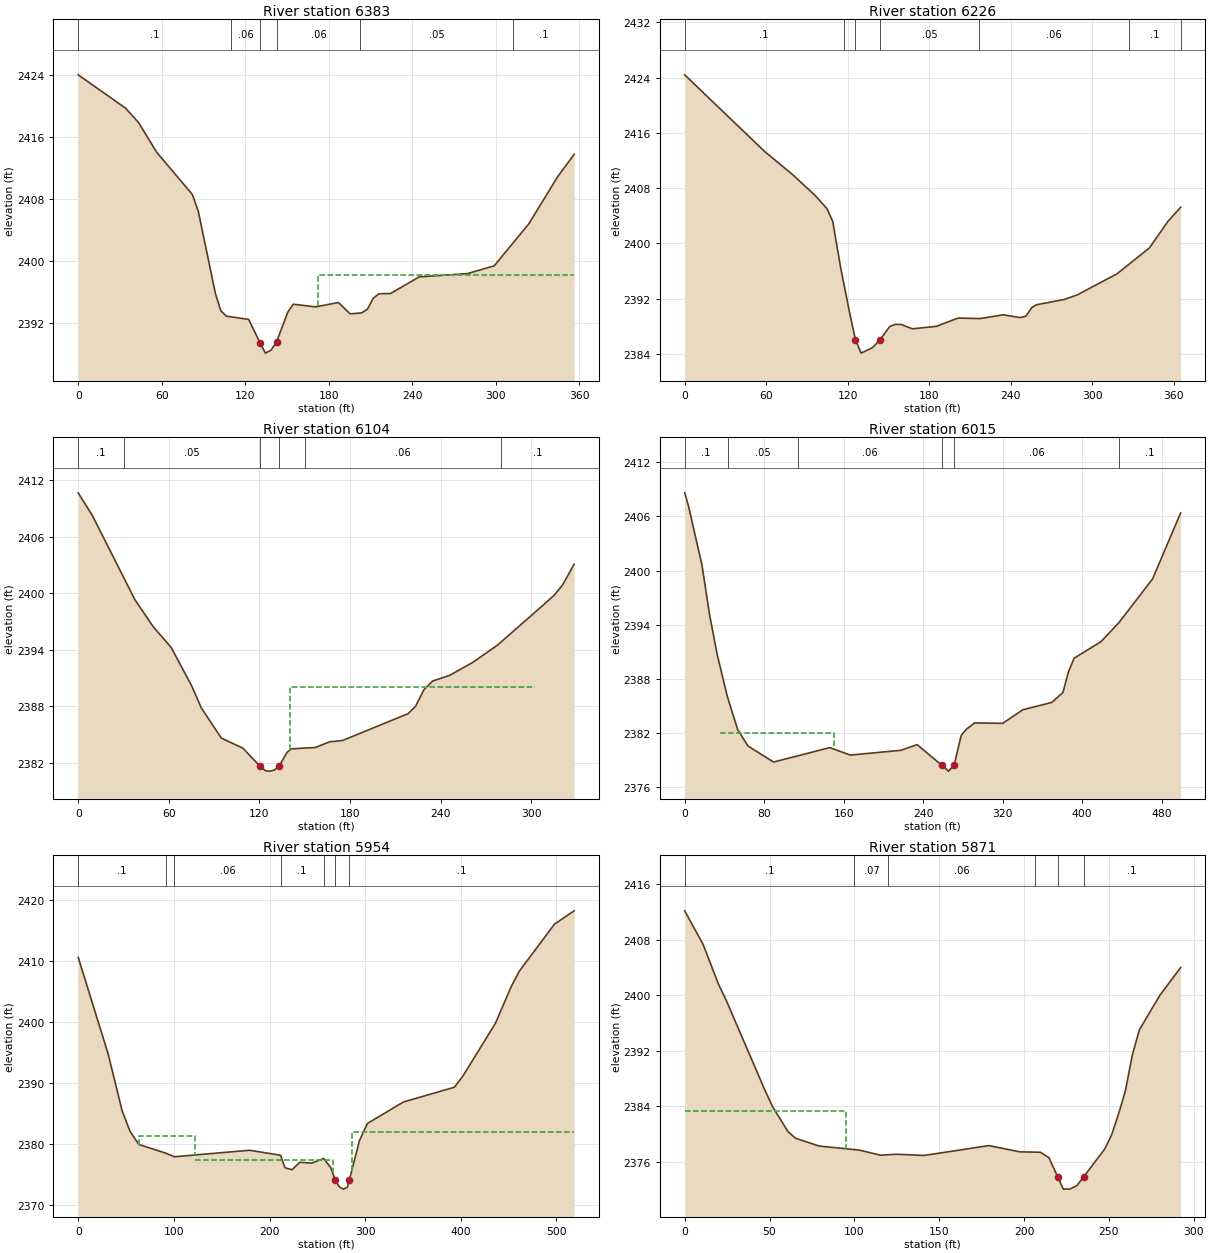
Type RM Length L Ch R = 1 ,6383    ,157.3,157.3,157.3
XS GIS Cut Line= 4
2216680.91879407443440.2246220072216596.99587191443408.668294642
2216514.00670994443407.7058262482216336.81864442443455.788838437
#Sta/Elev= 30
       0 2424.01      34 2419.71    43.3 2417.87    56.3 2414.04      82 2408.57
    86.3 2406.39    98.5 2395.84   102.5 2393.55   106.5 2392.87   122.5 2392.45
   130.5 2389.47   134.5  2388.1   138.5 2388.48   142.5 2389.55   150.5 2393.36
   154.5 2394.41   170.5 2394.07     187 2394.63   195.3 2393.17   203.6 2393.29
   207.7 2393.75   211.9 2395.17     216 2395.76   224.4 2395.79     245 2397.94
   279.7 2398.36   298.9 2399.37   323.8  2404.8   344.5 2410.88   356.3 2413.75
#Mann= 6 ,-1,0
       0      .1       0  109.66     .06       0   130.5    .045       0
   142.5     .06       0  202.65     .05       0  312.65      .1       0
#XS Ineff= 2 , 0
                          172.39         2398.22
Permanent Ineff=
       F       F
Bank Sta=130.5,142.5
XS Rating Curve= 0 ,0
Exp/Cntr(USF)=0,0
Exp/Cntr=0.3,0.1

Type RM Length L Ch R = 1 ,6226    ,121.5,121.5,121.5
XS GIS Cut Line= 3
2216692.43994394443270.5137922462216599.61120678443242.246394842
2216343.45972907443321.115923401
#Sta/Elev= 30
       0 2424.39    58.8  2413.3    79.7  2409.9    96.4 2406.85   104.8    2405
     109 2403.16   114.9  2396.4   121.3 2390.05   125.7 2386.04   129.9 2384.09
   138.3 2384.89   143.7 2385.98   150.9 2387.94     155 2388.25   159.2 2388.25
   167.6 2387.61   185.3 2387.97   201.3 2389.17   217.3 2389.09   234.6 2389.64
   247.1 2389.23   251.3 2389.46   255.5 2390.68   258.9 2391.09   279.2 2391.85
     289 2392.52   318.3 2395.58   342.1 2399.32   355.9  2403.2   365.1 2405.21
#Mann= 7 ,-1,0
       0      .1       0  117.04     .05       0   125.7    .045       0
   143.7     .05       0  217.04     .06       0  327.04      .1       0
  365.06     .05       0
Bank Sta=125.7,143.7
XS Rating Curve= 0 ,0
Exp/Cntr(USF)=0,0
Exp/Cntr=0.3,0.1

Type RM Length L Ch R = 1 ,6104    ,89.3,89.3,89.3
BEGIN DESCRIPTION:
structure xs 4
END DESCRIPTION:
XS GIS Cut Line= 3
2216613.60404777443124.719760378 2216523.7868881443128.418231136
2216346.45164357443287.780735381
#Sta/Elev= 30
       0 2410.67     9.4 2408.25    37.5 2399.32    49.5 2396.47    61.5 2394.24
    74.9 2390.22    81.5 2387.81    94.7 2384.61     109 2383.53120.44942381.596
   124.1 2381.12   126.9 2381.09   129.8  2381.2132.97942381.612   138.3  2383.1
   141.1 2383.46   156.9  2383.6   166.6 2384.21   175.1 2384.35   218.4  2387.2
   223.3 2387.98   228.9 2389.75   234.6 2390.66   245.9 2391.27   261.5 2392.68
   277.6 2394.49   309.9 2399.03   315.2 2399.81   320.6 2400.87   328.3 2403.08
#Mann= 6 ,-1,0
       0      .1       0      30     .05       0120.4494    .045       0
132.9794     .05       0  149.89     .06       0  279.89      .1       0
#XS Ineff= 1 ,-1
  140.32302.2341 2390.02
Permanent Ineff=
       F
Bank Sta=120.4494,132.9794
XS Rating Curve= 0 ,0
Exp/Cntr(USF)=0,0
Exp/Cntr=0.5,0.3

Type RM Length L Ch R = 1 ,6015    ,60.7,60.7,60.7
BEGIN DESCRIPTION:
structure xs 3; 17 ft between structure and xs
END DESCRIPTION:
XS GIS Cut Line= 6
2216565.70444871442901.5109031282216420.59821261443018.880694635
2216434.74458628443087.7131788742216422.87227937 443102.12955155
2216437.86425512443180.5599278512216336.14195054443281.594919562
#Sta/Elev= 30
       0 2408.62     3.7 2407.22    17.4  2400.6    24.9 2395.19    32.8 2390.63
    43.1 2385.95    53.4 2382.33    63.7 2380.53    89.4 2378.75     114 2379.44
   145.9 2380.35   166.6 2379.52   217.6 2380.05   233.9 2380.68   258.8 2378.38
   265.5 2377.74   271.1 2378.41   278.2 2381.68     283 2382.35   291.8 2383.09
     320 2383.04   340.2 2384.55   369.3 2385.36   380.6 2386.47   386.2 2388.78
   391.9 2390.27     419 2392.12     437 2394.23   470.8 2399.07     499 2406.39
#Mann= 6 ,-1,0
       0      .1       0    43.1     .05       0     114     .06       0
   258.8    .045       0   271.1     .06       0     437      .1       0
#XS Ineff= 3 ,-1
   35.21     1502381.966     150     224  2378.9   292.8 494.055  2381.9
Permanent Ineff=
       F       F       F
Bank Sta=258.8,271.1
XS Rating Curve= 0 ,0
Exp/Cntr(USF)=0,0
Exp/Cntr=0.5,0.3

Type RM Length L Ch R = 1 ,5954    ,82.9,82.9,82.9
BEGIN DESCRIPTION:
structure xs 2; 7.6 ft between structure and xs
END DESCRIPTION:
XS GIS Cut Line= 6
2216567.07907445442885.3590507112216380.12997414442993.954483978
2216388.95140249443041.0719731572216377.64444352443071.600762354
2216386.65440564443167.7886980782216297.65242989443255.820686982
#Sta/Elev= 30
       0 2410.56    31.3 2394.72    45.9  2385.4    54.2 2382.01    63.4 2379.85
    91.3 2378.45   100.5 2377.84   179.1 2378.91   211.5 2378.09   216.2 2376.03
   223.6 2375.72   231.7 2376.94   243.9 2376.79   256.7 2377.56   264.1 2376.04
   268.5 2374.08   272.8 2372.94   277.3 2372.53   281.3 2372.82   283.5 2374.05
   294.1 2380.51   302.3  2383.3     340 2386.83   393.3 2389.25   402.4 2391.13
   436.2 2399.75   452.6 2405.73   461.1 2408.28   497.9 2416.01   518.5  2418.2
#Mann= 7 ,-1,0
       0      .1       0    91.3     .05       0   100.5     .06       0
   211.5      .1       0   256.7     .06       0   268.5    .045       0
   283.5      .1       0
#XS Ineff= 3 ,-1
   63.59  121.66 2381.21  121.66     266  2377.3     286   518.5  2381.9
Permanent Ineff=
       F       F       F
Bank Sta=268.5,283.5
XS Rating Curve= 0 ,0
Exp/Cntr(USF)=0,0
Exp/Cntr=0.5,0.3

Type RM Length L Ch R = 1 ,5871    ,322.7,322.7,322.7
BEGIN DESCRIPTION:
structure xs 1
END DESCRIPTION:
XS GIS Cut Line= 3
2216565.70444871442871.2691369012216384.25385135442969.554877137
2216300.40168136442988.112324594
#Sta/Elev= 30
       0  2412.2    10.8 2407.39    19.9 2401.64    24.5 2399.28    47.2 2386.37
    51.8 2383.95    60.9 2380.35    65.4 2379.39    79.3 2378.27   102.9 2377.69
   115.5 2376.95   124.6 2377.09   141.2 2376.92   179.2 2378.34   197.4 2377.44
   209.5 2377.38   214.6 2376.61  219.752373.848   223.1 2372.06   226.9 2372.07
     231 2372.55   235.1 2373.85   247.4 2377.82   251.5 2379.86   255.6 2382.88
   259.6 2386.17   263.8 2391.46   267.9 2395.03   279.9 2399.99   292.2 2404.02
#Mann= 6 ,-1,0
       0      .1       0     100     .07       0     120     .06       0
  206.36      .1       0  219.75    .045       0   235.1      .1       0
#XS Ineff= 2 , 0
           94.93 2383.33
Permanent Ineff=
       F       F
Bank Sta=219.75,235.1
XS Rating Curve= 0 ,0
Exp/Cntr(USF)=0,0
Exp/Cntr=0.3,0.1

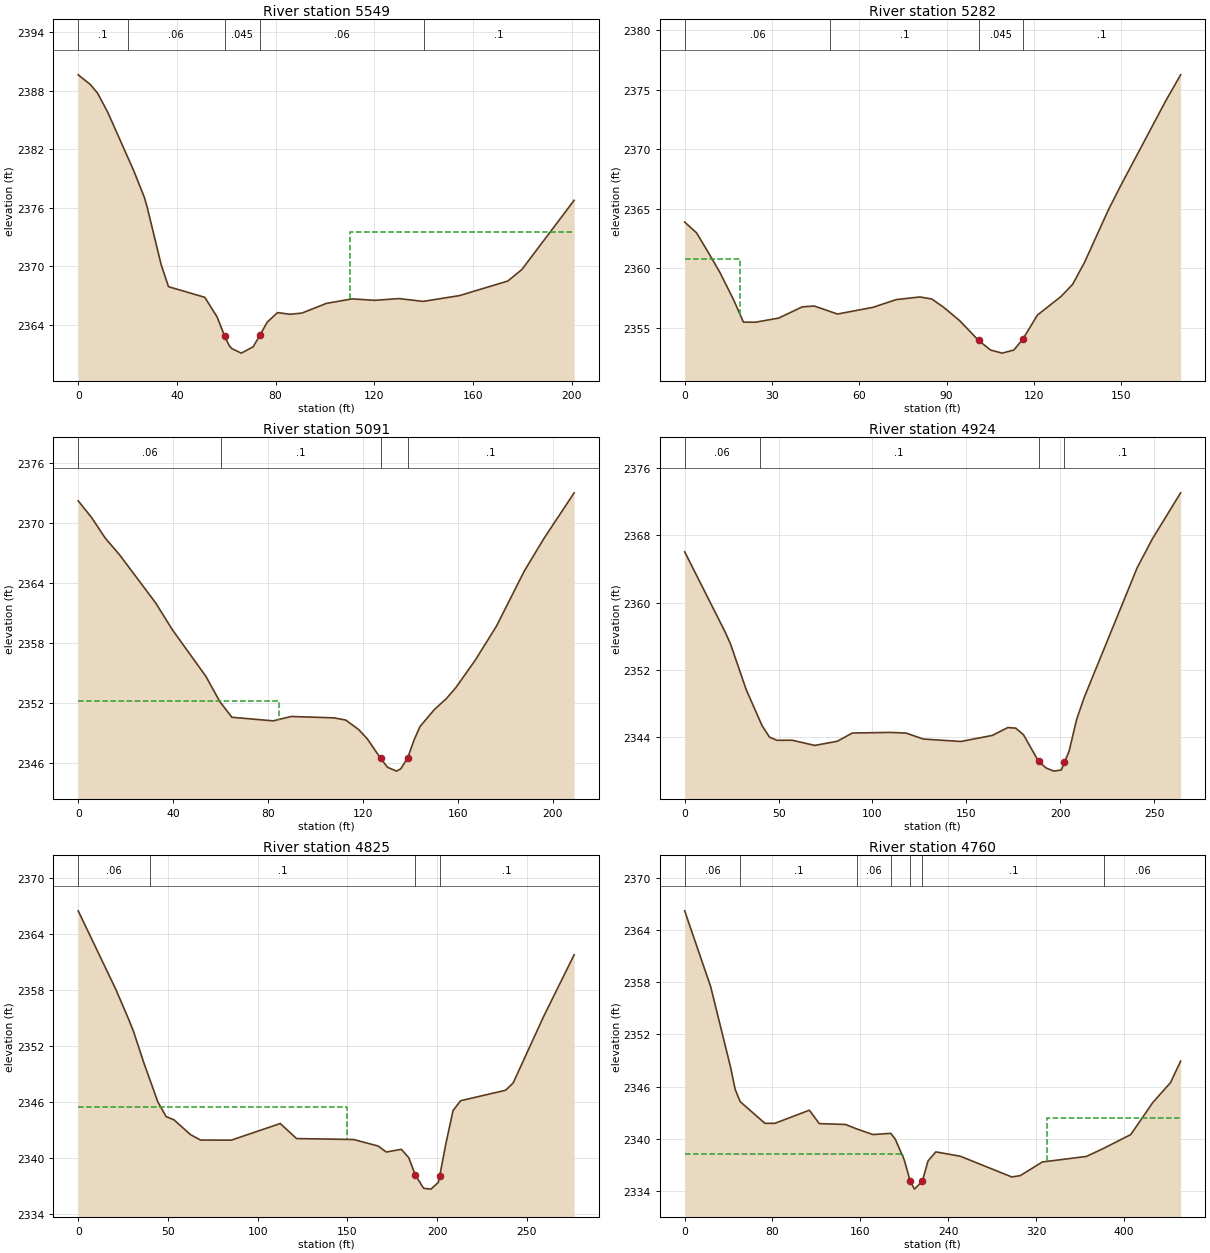
Type RM Length L Ch R = 1 ,5549    ,267.1,267.1,267.1
XS GIS Cut Line= 2
2216401.95343065 442620.103444212216238.37296788442736.946631902
#Sta/Elev= 30
       0 2389.64     4.9 2388.65     7.8 2387.78      12 2385.78    22.5  2379.8
    26.8 2377.07    27.9 2376.11    33.6 2370.17    36.6 2367.89    51.3  2366.8
    56.3 2364.78    59.4 2362.78    61.2 2361.84    62.3 2361.53    66.1 2361.07
    70.9 2361.72    73.7 2362.93    76.6 2364.25    80.8 2365.23    85.8 2365.06
    90.7 2365.18   100.5 2366.17     111 2366.64   120.2 2366.49     130 2366.67
   139.8 2366.38   154.6 2366.98   174.1 2368.47   179.8 2369.65     201 2376.76
#Mann= 5 ,-1,0
       0      .1       0      20     .06       0    59.4    .045       0
    73.7     .06       0     140      .1       0
#XS Ineff= 2 , 0
                          110.22         2373.46
Permanent Ineff=
       F       F
Bank Sta=59.4,73.7
XS Rating Curve= 0 ,0
Exp/Cntr(USF)=0,0
Exp/Cntr=0.3,0.1

Type RM Length L Ch R = 1 ,5282    ,190.3,190.3,190.3
XS GIS Cut Line= 2
2216332.19422881442451.9884576772216163.50703142442428.049350458
#Sta/Elev= 30
       0 2363.89     4.1 2362.98     8.1 2361.35    12.1 2359.67    16.7 2357.43
    20.2  2355.5    24.3 2355.49    32.3 2355.84    40.4 2356.78    44.5 2356.85
    52.5 2356.18    64.7 2356.74    72.7 2357.39    80.8 2357.61    84.9 2357.44
    88.9 2356.76    94.5 2355.62     101 2353.96   105.1 2353.16   109.1  2352.9
   113.1 2353.16  116.112354.048   121.2 2356.09   129.3 2357.65   133.3 2358.67
   137.4 2360.52   145.5 2364.87   149.5  2366.8   165.2 2374.02   170.4 2376.24
#Mann= 4 ,-1,0
       0     .06       0      50      .1       0     101    .045       0
  116.11      .1       0
#XS Ineff= 2 , 0
           19.08 2360.81
Permanent Ineff=
       F       F
Bank Sta=101,116.11
XS Rating Curve= 0 ,0
Exp/Cntr(USF)=0,0
Exp/Cntr=0.3,0.1

Type RM Length L Ch R = 1 ,5091    ,166.9,166.9,166.9
XS GIS Cut Line= 3
2216395.71539535442373.6793589922216294.37690562442259.192685815
2216239.79143035442245.973442788
#Sta/Elev= 30
       0  2372.2     5.7 2370.51    11.4 2368.47    17.4 2366.81    32.7 2361.97
    39.7  2359.3    53.9 2354.61    59.7 2352.11    64.8 2350.54    82.2 2350.18
    89.8 2350.62   107.9 2350.48   112.8 2350.26   118.2 2349.32   121.9 2348.38
   127.5 2346.43   130.4 2345.54   134.2 2345.15     136 2345.38   138.9 2346.47
   141.7 2348.32   144.1 2349.61   150.2 2351.32   155.2  2352.4   159.3 2353.53
   167.5 2356.29   176.3 2359.64   188.1 2365.18   196.3 2368.41   209.1    2373
#Mann= 4 ,-1,0
       0     .06       0      60      .1       0   127.5    .045       0
   138.9      .1       0
#XS Ineff= 2 , 0
           84.49 2352.13
Permanent Ineff=
       F       F
Bank Sta=127.5,138.9
XS Rating Curve= 0 ,0
Exp/Cntr(USF)=0,0
Exp/Cntr=0.3,0.1

Type RM Length L Ch R = 1 ,4924    ,99.8,99.8,99.8
XS GIS Cut Line= 5
2216515.40598243 442127.671657242216476.00591188442115.194968234
2216413.62246685442109.9416254942216341.38900418442130.954996453
2216257.33552034442118.478307446
#Sta/Elev= 30
       0 2366.05    21.5 2356.52    24.4 2355.08    32.8 2349.62    41.2 2345.35
    45.2 2343.97    49.2  2343.6    57.2 2343.61    69.3 2342.99    81.3 2343.49
    89.3 2344.47   109.6 2344.54   117.9 2344.46   127.1 2343.75   147.1 2343.46
   163.8 2344.18   172.1 2345.12   176.3 2345.05   180.4 2344.27   188.5 2341.08
   192.5  2340.3   196.6 2339.93   200.6 2340.07   202.2 2340.97   204.7 2342.29
   208.7 2346.07   212.7 2348.67     241 2364.17   249.1  2367.6   264.1 2373.07
#Mann= 4 ,-1,0
       0     .06       0      40      .1       0   188.5    .045       0
   202.2      .1       0
Bank Sta=188.5,202.2
XS Rating Curve= 0 ,0
Exp/Cntr(USF)=0,0
Exp/Cntr=0.3,0.1

Type RM Length L Ch R = 1 ,4825    ,67.4,67.4,67.4
BEGIN DESCRIPTION:
structure xs 4
END DESCRIPTION:
XS GIS Cut Line= 4
2216519.25329918442118.5111268752216366.71108108442036.116060166
2216317.16269637442023.8681448452216268.17103508 442041.12657098
#Sta/Elev= 30
       0 2366.47      21 2358.05    28.1 2354.87    30.8 2353.58    36.5 2350.25
    44.4 2346.01      49 2344.45    53.4  2344.1    62.6 2342.52    68.2 2341.94
    85.3 2341.93   112.6 2343.71   121.7  2342.1   153.5    2342   167.2  2341.3
   171.7 2340.66   180.1 2340.95   184.2 2340.06   187.8 2338.23   192.5 2336.78
   196.6 2336.69   200.7 2337.41  201.462338.095   204.8 2341.45   208.9 2345.09
   213.1 2346.15   238.2 2347.27   242.4 2348.05   259.4 2355.17   276.4 2361.77
#Mann= 4 ,-1,0
       0     .06       0      40      .1       0   187.8    .045       0
  201.46      .1       0
#XS Ineff= 2 , 0
          149.75 2345.51
Permanent Ineff=
       F       F
Bank Sta=187.8,201.46
XS Rating Curve= 0 ,0
Exp/Cntr(USF)=0,0
Exp/Cntr=0.5,0.3

Type RM Length L Ch R = 1 ,4760    ,37.4,37.4,37.4
BEGIN DESCRIPTION:
structure xs 3; 6.2 ft between structure and xs
END DESCRIPTION:
XS GIS Cut Line= 6
2216521.20183116442109.3251903842216391.48527343442042.518379539
2216383.62048467441994.3966341372216376.02097555441963.114933802
2216369.77305991441898.3270127982216211.10688415441879.398416392
#Sta/Elev= 30
       0  2366.2    23.7 2357.48    41.6 2348.34    46.1 2345.64    50.6 2344.27
    73.1 2341.78    82.1 2341.78   113.6 2343.29   122.6 2341.75   146.5 2341.65
   156.9 2341.13   171.6 2340.49   187.8 2340.63   191.9 2339.95     200 2337.59
205.40682335.167   209.3 2334.22   216.5 2335.14   221.7 2337.46   228.8  2338.5
   251.1    2338     298 2335.62   305.7 2335.77   325.8 2337.34   366.1 2337.98
   382.2 2338.94   406.4 2340.49   426.5 2344.18   442.6 2346.46   451.8 2348.93
#Mann= 7 ,-1,0
       0     .06       0    50.6      .1       0   156.9     .06       0
   187.8      .1       0205.4068    .045       0   216.5      .1       0
   382.2     .06       0
#XS Ineff= 3 ,-1
       0     199  2338.3   222.7  247.89  2335.1  329.92   451.82342.397
Permanent Ineff=
       F       F       F
Bank Sta=205.4068,216.5
XS Rating Curve= 0 ,0
Exp/Cntr(USF)=0,0
Exp/Cntr=0.5,0.3

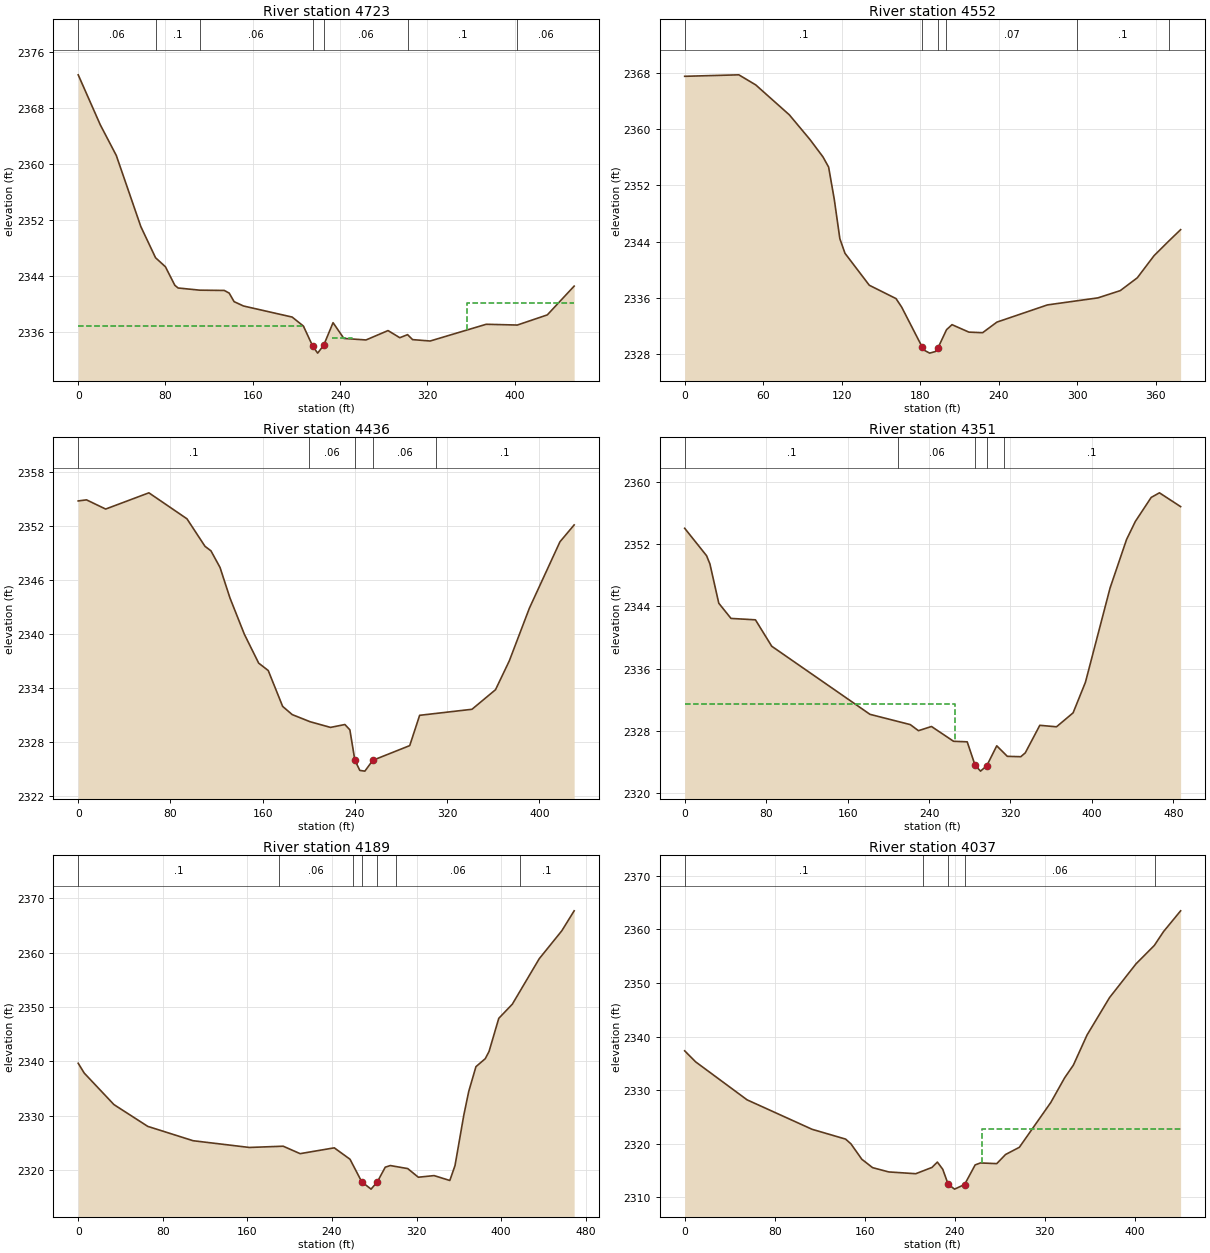
Type RM Length L Ch R = 1 ,4723    ,170.3,170.3,170.3
BEGIN DESCRIPTION:
structure xs 2; 8.2 ft between structure and xs
END DESCRIPTION:
XS GIS Cut Line= 6
 2216543.1924064442089.5615088422216413.47584867442022.754697997
2216405.88881372 441955.338691912216395.81504582441938.195613195
2216391.76363515441878.5633312572216233.09745939 441859.63473485
#Sta/Elev= 30
       0 2372.72    20.3 2365.56    34.9 2361.21    57.4 2351.05    70.9  2346.6
    79.9 2345.32    88.6 2342.66    91.6 2342.28   111.4 2341.97   133.9 2341.93
   138.4 2341.55   142.9 2340.33   151.5 2339.71   196.1 2338.13   206.4 2336.85
     215 2333.96   219.5 2332.98     225  2334.1   233.6 2337.33   243.5 2335.08
   263.8 2334.86     284  2336.2   294.8 2335.18   301.9 2335.62   306.5 2334.91
   322.6 2334.71     374  2337.1   402.5 2336.99     430 2338.44   454.6 2342.55
#Mann= 7 ,-1,0
       0     .06       0    70.9      .1       0   111.4     .06       0
     215    .045       0     225     .06       0   301.9      .1       0
   402.5     .06       0
#XS Ineff= 3 ,-1
       0     207  2336.8     233  250.99  2335.1  356.37   454.62340.176
Permanent Ineff=
       F       F       F
Bank Sta=215,225
XS Rating Curve= 0 ,0
Exp/Cntr(USF)=0,0
Exp/Cntr=0.5,0.3

Type RM Length L Ch R = 1 ,4552    ,116.2,116.2,116.2
BEGIN DESCRIPTION:
structure xs 1
END DESCRIPTION:
XS GIS Cut Line= 2
2216566.78541195441713.3199602332216213.27415642441849.910967908
#Sta/Elev= 30
       0 2367.47    41.4 2367.68    54.3 2366.25      80    2362    95.7 2358.51
   105.7 2356.03     110 2354.59   114.3 2350.04   118.6 2344.42   122.5 2342.36
   141.1 2337.82   161.5 2335.93   165.8 2334.73   181.3 2329.13   182.9 2328.62
   187.2 2328.19   191.5 2328.41   193.7 2328.98   200.1 2331.51   204.3 2332.23
   217.2 2331.17   227.7 2331.09   238.6 2332.59   277.2 2335.03   315.8 2336.03
   332.9 2337.06   345.9 2338.88   358.7 2342.02     370  2344.1     379 2345.71
#Mann= 6 ,-1,0
       0      .1       0   181.3    .045       0   193.7      .1       0
     200     .07       0     300      .1       0     370     .06       0
Bank Sta=181.3,193.7
XS Rating Curve= 0 ,0
Exp/Cntr(USF)=0,0
Exp/Cntr=0.3,0.1

Type RM Length L Ch R = 1 ,4436    ,84.8,84.8,84.8
XS GIS Cut Line= 4
2216579.10276315441608.904061697 2216357.1490324441669.974171045
2216275.72221993441703.4642310112216164.08868671441710.030909435
#Sta/Elev= 30
       0 2354.77     7.2 2354.89    23.8 2353.87    61.3 2355.67    94.3 2352.79
     110 2349.73   115.1 2349.24     123 2347.39   131.6 2344.01   144.1 2339.98
   156.5 2336.78   164.8 2335.96   177.3 2331.98   185.6 2331.07   201.1 2330.28
   218.8 2329.65   231.3 2329.97   235.6 2329.38   239.9 2326.03   244.2 2324.88
   248.6  2324.8   255.5    2326   287.5 2327.63   296.1 2330.99   341.5 2331.66
   361.9 2333.83   373.9 2337.04   391.3 2342.88   417.8 2350.24   430.1 2352.11
#Mann= 5 ,-1,0
       0      .1       0     200     .06       0   239.9    .045       0
   255.5     .06       0   310.2      .1       0
Bank Sta=239.9,255.5
XS Rating Curve= 0 ,0
Exp/Cntr(USF)=0,0
Exp/Cntr=0.3,0.1

Type RM Length L Ch R = 1 ,4351    ,162.4,162.4,162.4
XS GIS Cut Line= 4
2216589.70978051441580.8785283912216356.57137995441576.681206544
2216234.69820122441631.4556688932216115.58384862441614.317483847
#Sta/Elev= 30
       0 2354.01    21.5 2350.49    24.8 2349.43    33.5 2344.39    45.5 2342.44
    69.5 2342.26    85.5 2338.87     182 2330.13   221.6 2328.81   229.6 2328.03
   242.4 2328.57   264.1 2326.67   277.5  2326.6   285.3 2323.57   290.6 2322.84
   296.7 2323.53   306.5 2326.09   316.9 2324.74   330.1 2324.69   334.5 2325.18
   348.8 2328.72   365.2 2328.53   381.5 2330.32   393.6 2334.24   417.8 2346.34
     434 2352.57   442.6 2354.88   458.2 2357.97   466.3 2358.56   487.1 2356.79
#Mann= 5 ,-1,0
       0      .1       0     210     .06       0   285.3    .045       0
   296.7     .06       0  313.18      .1       0
#XS Ineff= 2 , 0
          265.74  2331.4
Permanent Ineff=
       F       F
Bank Sta=285.3,296.7
XS Rating Curve= 0 ,0
Exp/Cntr(USF)=0,0
Exp/Cntr=0.3,0.1

Type RM Length L Ch R = 1 ,4189    ,151.7,151.7,151.7
XS GIS Cut Line= 4
2216569.90941335441482.8238359442216349.92568613 441473.63048615
2216223.18879253 441380.383652522216137.16530517441348.863596082
#Sta/Elev= 30
       0 2339.64     5.7 2337.83    33.8 2332.03    65.8 2328.02   108.7 2325.38
   161.9 2324.14   193.9 2324.37   209.9    2323   242.2 2324.07   257.1 2321.97
   268.2 2317.81     277 2316.47  282.96 2317.81   290.4 2320.51   295.2 2320.81
   311.7 2320.25   321.7 2318.66   336.6 2318.96   351.5 2318.06   356.4  2320.8
   364.8 2330.16   369.4 2334.46   376.2 2339.01     385 2340.48   388.6 2341.81
   397.8 2347.91   410.6 2350.51   436.1 2358.89   457.4 2364.02   469.1  2367.7
#Mann= 7 ,-1,0
       0      .1       0     190     .06       0  260.18      .1       0
   268.2    .045       0  282.96      .1       0  300.18     .06       0
  417.52      .1       0
Bank Sta=268.2,282.96
XS Rating Curve= 0 ,0
Exp/Cntr(USF)=0,0
Exp/Cntr=0.3,0.1

Type RM Length L Ch R = 1 ,4037    ,133.1,133.1,133.1
XS GIS Cut Line= 4
 2216560.6062522441426.0514350822216445.57988127441361.691441821
2216323.70670254441280.8991098562216160.75267705441280.899109856
#Sta/Elev= 30
       0 2337.34     9.7 2335.29    55.5 2328.19   113.3 2322.69   143.1 2320.86
   147.9 2319.96   157.5  2317.1   167.1 2315.53   181.5 2314.73   205.5  2314.4
   219.9 2315.57   224.7 2316.57   229.5 2315.22   234.3 2312.42     240 2311.52
   248.9 2312.38   258.3 2316.04     263 2316.41   277.5 2316.28   285.3 2317.98
   297.6 2319.33   325.6 2327.71   337.8 2332.28   345.6 2334.66   357.8  2340.3
   377.8 2347.28   401.3 2353.57   417.6 2357.01   425.8  2359.6     441 2363.48
#Mann= 5 ,-1,0
       0      .1       0  211.81     .06       0   234.3    .045       0
   248.9     .06       0  418.03      .1       0
#XS Ineff= 2 , 0
                          264.21         2322.68
Permanent Ineff=
       F       F
Bank Sta=234.3,248.9
XS Rating Curve= 0 ,0
Exp/Cntr(USF)=0,0
Exp/Cntr=0.3,0.1