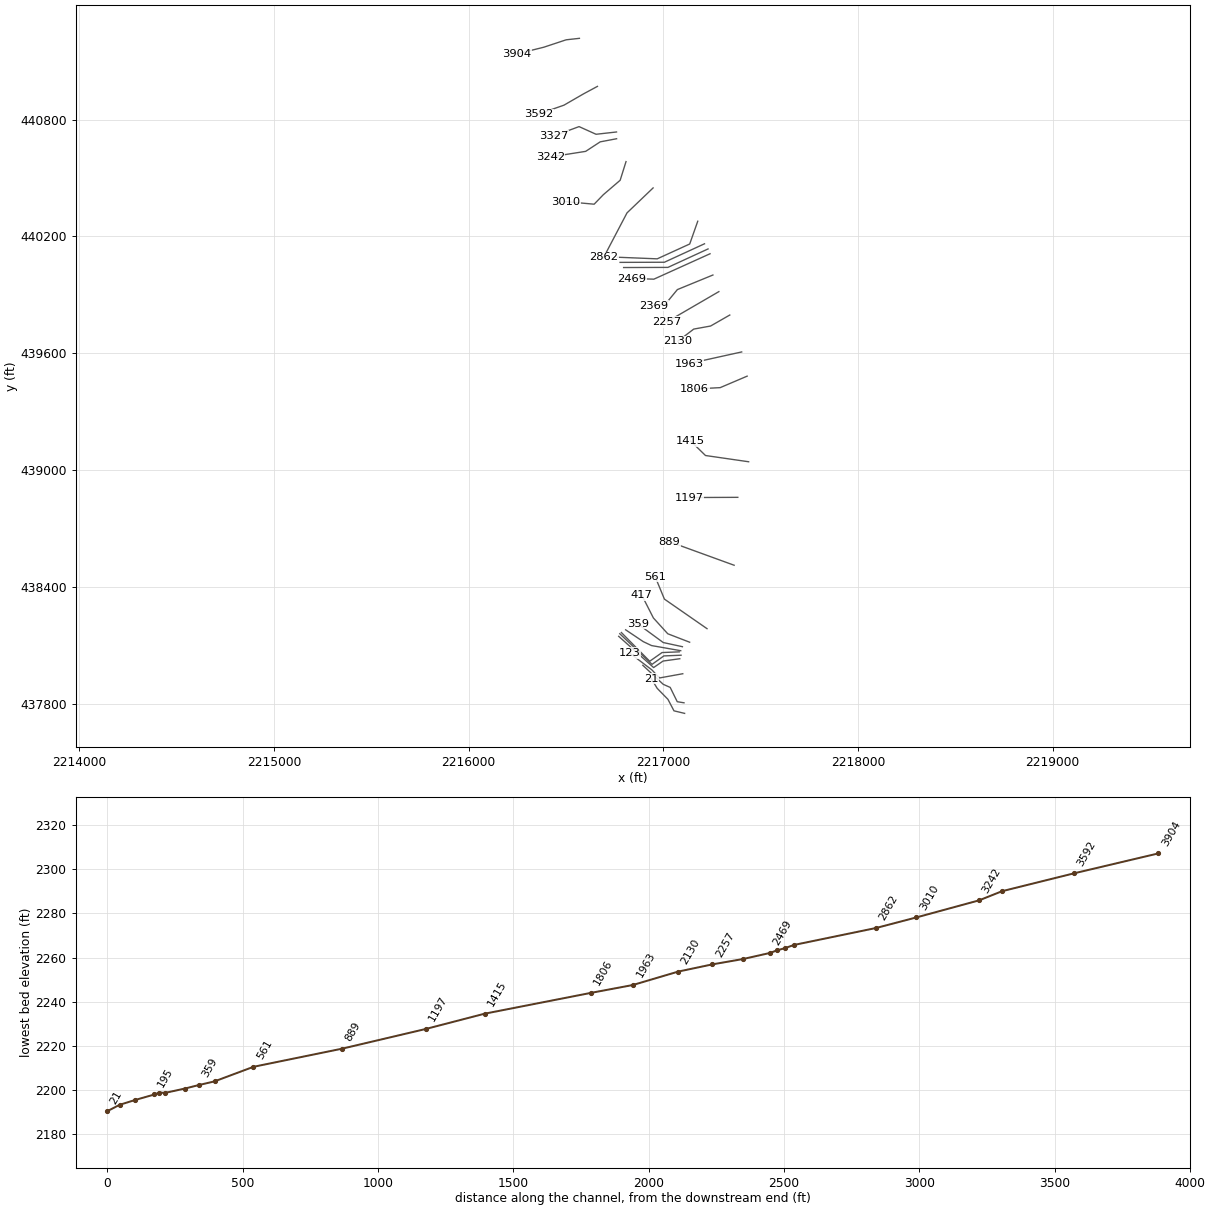
HEC-RAS study DRYCK.prj: DRYCK

--- DRYCK.g01 (geometry) --- (continued)

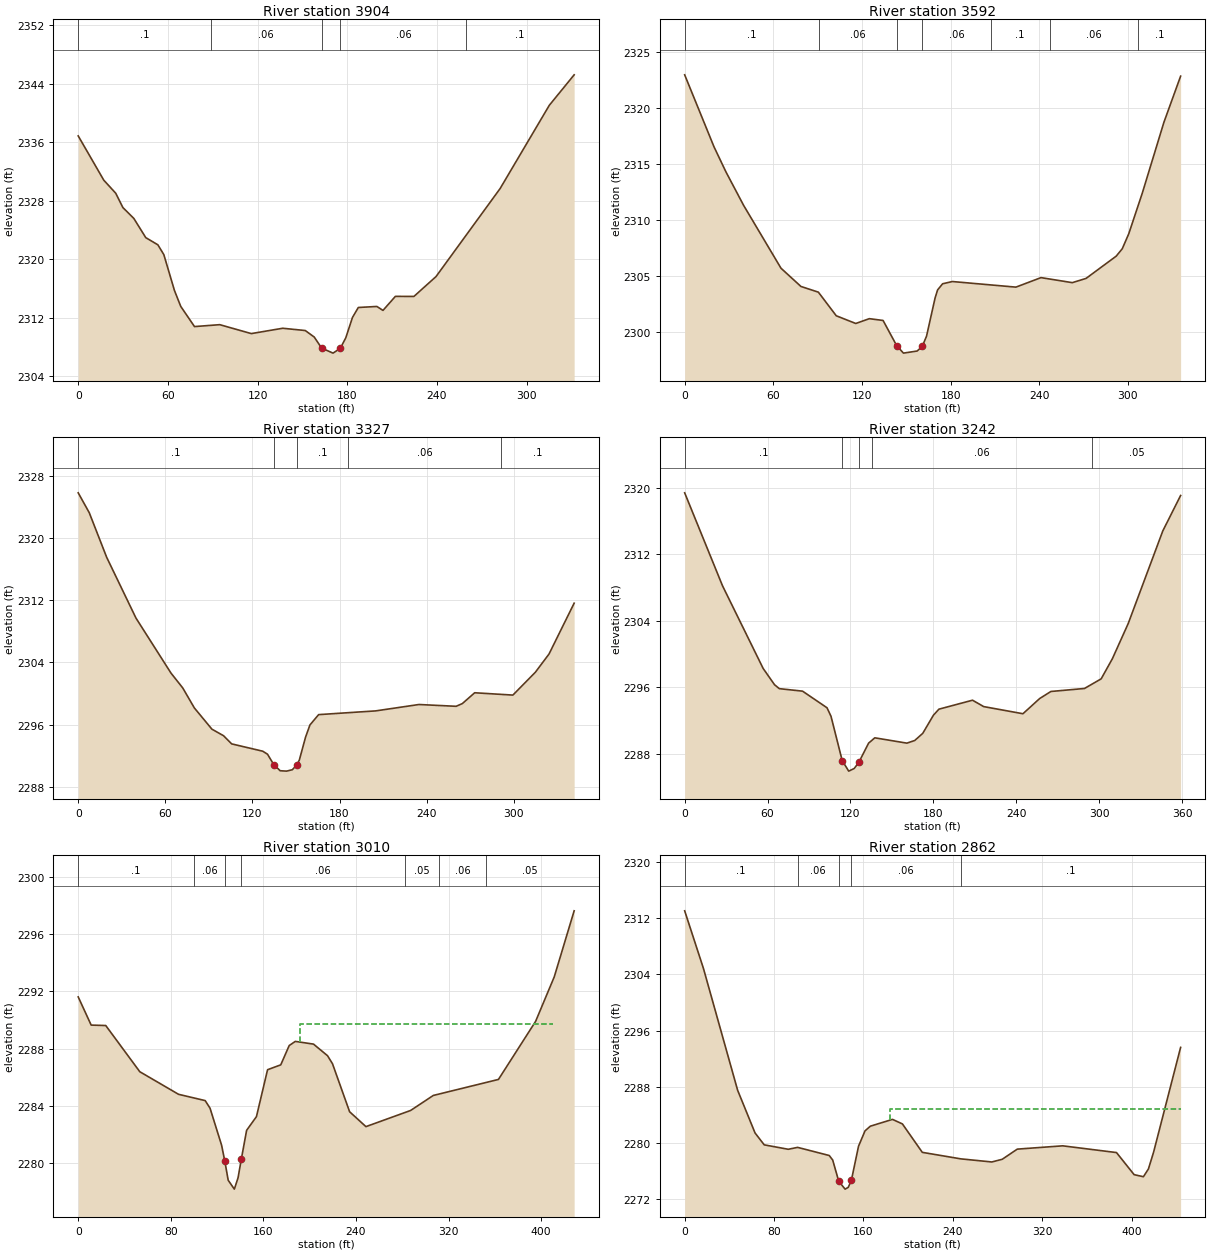
Type RM Length L Ch R = 1 ,3904    ,312.5,312.5,312.5
XS GIS Cut Line= 4
2216569.12640982441217.2135156312216500.95928989441209.650013481
2216386.04241746441171.5632786182216248.14230258441137.197804664
#Sta/Elev= 30
       0 2336.84    17.1 2330.79    25.1    2329    29.9 2327.04    37.2 2325.56
    45.2 2322.93    53.3 2321.95    57.3  2320.6    64.4  2315.7    68.6 2313.53
    77.8 2310.77    94.7 2311.03   115.8 2309.81   136.8 2310.54   151.9 2310.23
   157.9 2309.34162.88882307.823   170.5 2307.14  175.39 2307.81     179 2309.23
   183.5 2312.02   187.4 2313.38   199.8 2313.52   203.9 2312.98   212.2  2314.9
   224.6 2314.89   239.4 2317.61   282.3 2329.65   315.2 2341.03   331.8 2345.19
#Mann= 5 ,-1,0
       0      .1       0   88.59     .06       0162.8888    .045       0
  175.39     .06       0  259.65      .1       0
Bank Sta=162.8888,175.39
XS Rating Curve= 0 ,0
Exp/Cntr(USF)=0,0
Exp/Cntr=0.3,0.1

Type RM Length L Ch R = 1 ,3592    ,265.1,265.1,265.1
XS GIS Cut Line= 4
2216661.62744279440970.3907186732216590.62135052440932.176125514
2216489.80089961440873.9400189372216359.03385709440827.956003985
#Sta/Elev= 30
       0 2322.98    19.8 2316.56    27.9 2314.31    39.9 2311.31    65.2 2305.69
    78.7 2304.06    90.5 2303.55   102.6 2301.44   115.8 2300.75     125 2301.18
   134.3 2301.02   143.5 2298.77   148.1  2298.1   157.4 2298.29   160.8  2298.7
   163.7 2299.61   169.5 2303.03   171.2 2303.75   174.6  2304.3   181.2  2304.5
   224.2    2304   241.2 2304.85   262.4  2304.4   271.7 2304.78   292.1 2306.77
   296.2 2307.43   300.6 2308.77   309.7 2312.38   324.4 2318.74   335.7 2322.86
#Mann= 7 ,-1,0
       0      .1       0   90.64     .06       0   143.5    .045       0
   160.8     .06       0  207.07      .1       0  247.07     .06       0
  307.07      .1       0
Bank Sta=143.5,160.8
XS Rating Curve= 0 ,0
Exp/Cntr(USF)=0,0
Exp/Cntr=0.3,0.1

Type RM Length L Ch R = 1 ,3327    ,84.8,84.8,84.8
XS GIS Cut Line= 4
2216759.68641982440736.1924990662216654.61956503440724.372477902
2216567.28274198 440763.772548452216435.94917349440715.179128108
#Sta/Elev= 30
       0  2325.8     7.6 2323.25    19.6 2317.52    39.8  2309.7    63.9 2302.64
      72 2300.73      80 2298.16    92.1 2295.43   100.1 2294.59   105.7 2293.54
   127.1  2292.6   130.4 2292.21   134.7 2290.88   139.1 2290.09   143.5 2290.04
   147.5 2290.22   150.5 2290.83   152.3 2291.46   156.6 2294.41   159.6 2295.97
   165.6  2297.3   204.9 2297.78   234.7  2298.6   260.3 2298.37   264.6 2298.72
   273.1 2300.11   299.4 2299.81   314.9 2302.75   324.3 2305.09   341.6 2311.62
#Mann= 5 ,-1,0
       0      .1       0   134.7    .045       0   150.5      .1       0
  185.73     .06       0  291.54      .1       0
Bank Sta=134.7,150.5
XS Rating Curve= 0 ,0
Exp/Cntr(USF)=0,0
Exp/Cntr=0.3,0.1

Type RM Length L Ch R = 1 ,3242    ,231.9,231.9,231.9
XS GIS Cut Line= 4
2216760.01986364440701.4176590552216675.85034896440685.438985482
2216601.12632467440636.580969596 2216419.4507529440608.012628685
#Sta/Elev= 30
       0 2319.41    27.4 2308.21    56.8 2298.26      65 2296.31    68.5 2295.83
    85.3 2295.53     103 2293.53   105.9  2292.5     114 2287.17   118.7  2285.9
   122.7 2286.22   126.1 2286.98   133.1 2289.27   137.6 2289.91   160.8 2289.27
   166.5 2289.59   172.3 2290.45     180 2292.63     184 2293.36   208.3 2294.44
   216.4 2293.67   244.8 2292.81   256.9 2294.64     265 2295.49   289.3 2295.85
   301.4 2297.01   309.5 2299.43     321 2303.68     346 2314.82   358.9 2319.09
#Mann= 5 ,-1,0
       0      .1       0     114    .045       0   126.1      .1       0
  135.67     .06       0  294.95     .05       0
Bank Sta=114,126.1
XS Rating Curve= 0 ,0
Exp/Cntr(USF)=0,0
Exp/Cntr=0.3,0.1

Type RM Length L Ch R = 1 ,3010    ,148.2,148.2,148.2
XS GIS Cut Line= 5
2216808.46069434440583.8940764572216778.33474004440488.038767345
2216692.06496184440414.0932431732216644.76954739440365.175168076
2216498.98498206440378.489842646
#Sta/Elev= 30
       0 2291.61    11.2 2289.64    23.8 2289.61    53.2 2286.38    86.7  2284.8
   109.7 2284.36   113.9 2283.83   123.9 2281.24   126.7 2280.11   129.6 2278.79
   134.9 2278.17   138.1 2278.96   140.9 2280.25   145.5 2282.28     154 2283.24
   163.6 2286.52     175 2286.86   182.3 2288.21   187.6  2288.5   203.3 2288.31
   215.4  2287.5   219.7 2286.94   234.5 2283.58   248.6 2282.54   287.2 2283.67
   306.8 2284.72   363.1 2285.84   395.2  2289.9   411.3 2293.01   428.5 2297.63
#Mann= 7 ,-1,0
       0      .1       0     100     .06       0   126.7    .045       0
   140.9     .06       0  282.14     .05       0  312.14     .06       0
  352.14     .05       0
#XS Ineff= 1 ,-1
  192.01   410.4 2289.75
Permanent Ineff=
       F
Bank Sta=126.7,140.9
XS Rating Curve= 0 ,0
Exp/Cntr(USF)=0,0
Exp/Cntr=0.3,0.1

Type RM Length L Ch R = 1 ,2862    ,304.2,304.2,304.2
XS GIS Cut Line= 3
2216947.59053576440448.7595490672216813.53318291440320.521754789
 2216693.4925946440091.735398339
#Sta/Elev= 30
       0 2313.07    16.8 2304.86    47.4  2287.5      63 2281.41    71.2 2279.72
    92.7 2279.09   101.1 2279.36   129.4  2278.2   132.5 2277.55   137.9 2274.53
   143.6 2273.41   146.4 2273.66   149.2 2274.66   155.6 2279.52   161.4 2281.71
   166.2 2282.38     186 2283.35   194.9  2282.7   212.7 2278.65   247.3 2277.72
   274.9 2277.28   284.2 2277.66   297.7 2279.11   338.4 2279.58   386.5 2278.62
   402.3 2275.47   410.6 2275.18   415.1 2276.29   419.7 2278.67   443.9 2293.61
#Mann= 5 ,-1,0
       0      .1       0   101.1     .06       0   137.9    .045       0
   149.2     .06       0   247.3      .1       0
#XS Ineff= 2 , 0
                          183.38          2284.9
Permanent Ineff=
       F       F
Bank Sta=137.9,149.2
XS Rating Curve= 0 ,0
Exp/Cntr(USF)=0,0
Exp/Cntr=0.3,0.1

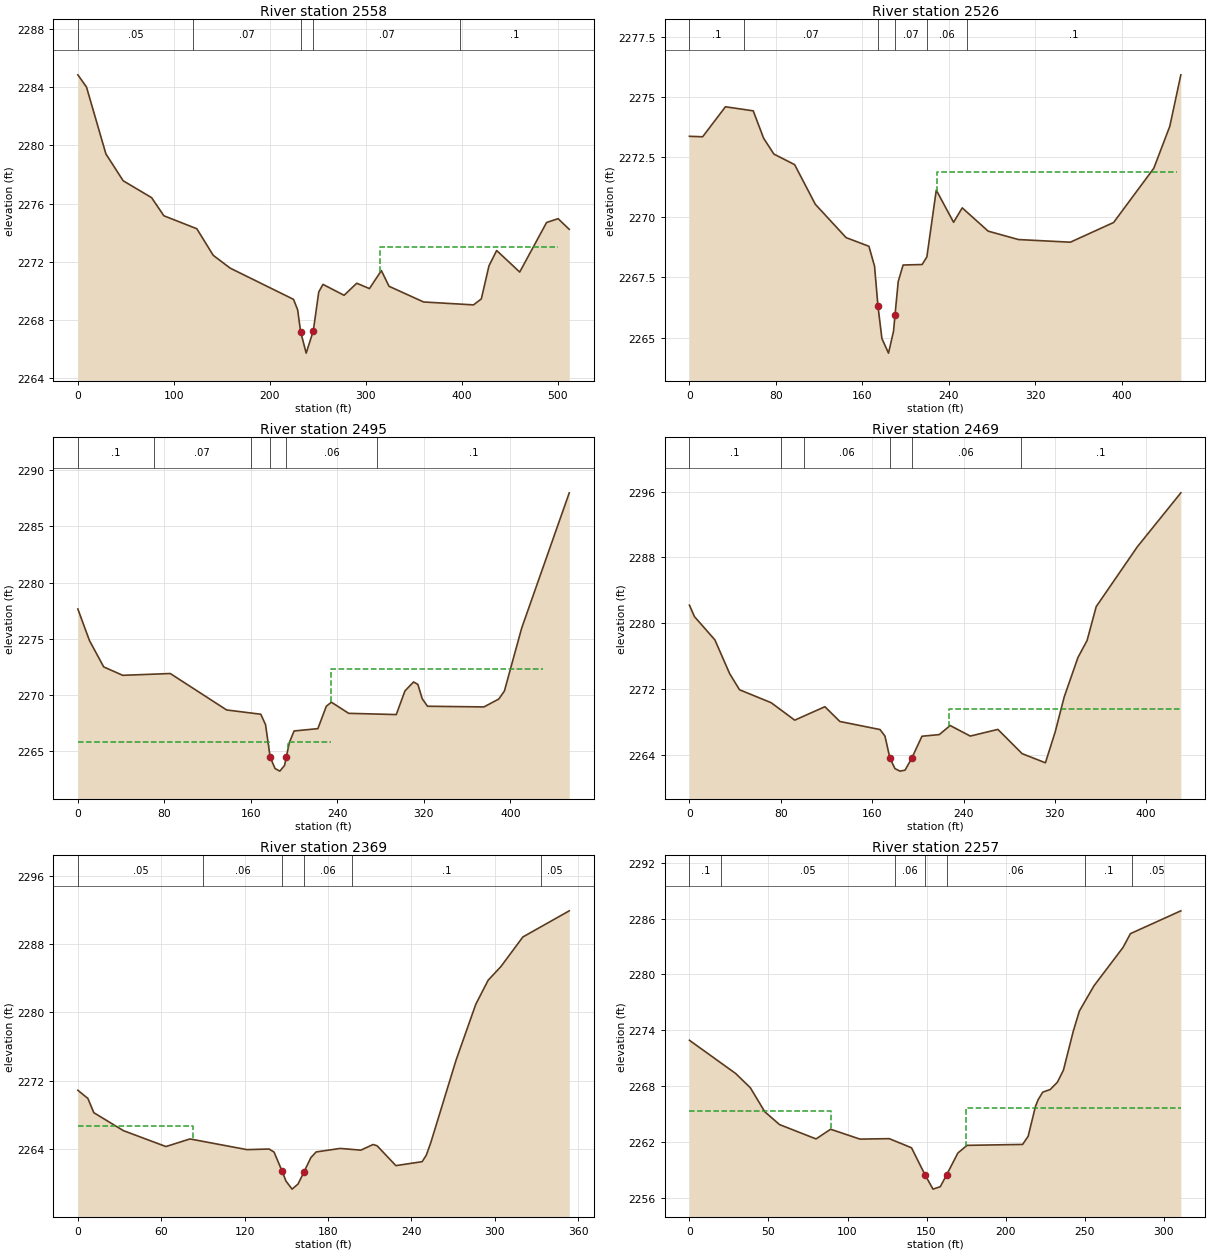
Type RM Length L Ch R = 1 ,2558    ,31.2,31.2,31.2
BEGIN DESCRIPTION:
structure xs 4
END DESCRIPTION:
XS GIS Cut Line= 4
 2217176.9689209440277.6466635842217135.73014877440160.803475892
2216968.71312166440084.5117474582216764.58119963440092.759501883
#Sta/Elev= 30
       0 2284.86       9 2284.02    29.2 2279.42    47.2 2277.57    76.8 2276.41
    89.6 2275.16   123.9 2274.27     141 2272.44   158.6 2271.56   224.6 2269.41
   228.9  2268.7     232 2267.19   237.8 2265.71   245.2 2267.24   250.9 2269.92
   255.3 2270.44   277.3 2269.69   290.5 2270.52   303.7 2270.15   316.1 2271.39
   324.1 2270.31   360.1 2269.23   412.1 2269.03   420.2 2269.44   428.2 2271.72
   436.2 2272.77   460.2 2271.29   488.2  2274.7   500.2 2274.96   511.8 2274.23
#Mann= 5 ,-1,0
       0     .05       0     120     .07       0     232    .045       0
   245.2     .07       0  397.52      .1       0
#XS Ineff= 1 ,-1
  315.04     500    2273
Permanent Ineff=
       F
Bank Sta=232,245.2
XS Rating Curve= 0 ,0
Exp/Cntr(USF)=0,0
Exp/Cntr=0.5,0.3

Type RM Length L Ch R = 1 ,2526    ,31.7,31.7,31.7
BEGIN DESCRIPTION:
structure xs 3; 8.4 ft between structure and xs
END DESCRIPTION:
XS GIS Cut Line= 3
2217211.67822077440161.8344451952217005.48436014440066.985269304
2216777.98380058440066.297956435
#Sta/Elev= 30
       0 2273.38    12.2 2273.36    33.3 2274.61      59 2274.44    68.6  2273.3
    78.1 2272.64    97.3  2272.2   116.4 2270.55   144.9 2269.16     166  2268.8
   171.2 2267.97  174.372266.306     178 2264.96   184.1 2264.35   188.8 2265.27
   190.1 2265.93   193.1 2267.33   197.6 2268.02   215.2 2268.04   219.6 2268.36
   228.3 2271.14   244.3  2269.8   252.3  2270.4   276.3 2269.43   304.3 2269.08
   352.3 2268.97   392.3 2269.79   429.5 2272.05   444.3  2273.8   454.5 2275.94
#Mann= 6 ,-1,0
       0      .1       0      50     .07       0  174.37    .045       0
   190.1     .07       0     220     .06       0  256.96      .1       0
#XS Ineff= 3 ,-1
       0     166  2265.8   198.5   229.3  2265.8   229.3   450.7 2271.89
Permanent Ineff=
       F       F       F
Bank Sta=174.37,190.1
XS Rating Curve= 0 ,0
Exp/Cntr(USF)=0,0
Exp/Cntr=0.5,0.3

Type RM Length L Ch R = 1 ,2495    ,25.6,25.6,25.6
BEGIN DESCRIPTION:
structure xs 2; 4.7 ft between structure and xs
END DESCRIPTION:
XS GIS Cut Line= 3
 2217229.8920118440135.3728997472217023.69815116440040.523723856
 2216796.1975916440039.836410987
#Sta/Elev= 30
       0 2277.66    10.7 2274.86    23.9 2272.51    41.5 2271.76    85.5 2271.92
   137.6 2268.68   169.2  2268.3   173.6 2267.37   177.9 2264.47   182.4 2263.47
   186.8 2263.24   191.2 2263.75   192.9 2264.54   195.6 2265.78     200 2266.81
     222 2267.02   229.8 2269.01   234.5 2269.37   250.5 2268.38   294.5 2268.27
   302.5 2270.37   310.5 2271.17   314.5 2270.95   318.5 2269.68   323.4 2269.01
   375.6 2268.95   389.3 2269.65   394.5 2270.36   410.5 2275.96   454.5 2287.99
#Mann= 6 ,-1,0
       0      .1       0      70     .07       0     160     .06       0
   177.9    .045       0   192.9     .06       0  276.96      .1       0
#XS Ineff= 3 ,-1
       0   176.4  2265.8   194.4  234.37  2265.8  234.37  429.86 2272.28
Permanent Ineff=
       F       F       F
Bank Sta=177.9,192.9
XS Rating Curve= 0 ,0
Exp/Cntr(USF)=0,0
Exp/Cntr=0.5,0.3

Type RM Length L Ch R = 1 ,2469    ,100,100,100
BEGIN DESCRIPTION:
structure xs 1
END DESCRIPTION:
XS GIS Cut Line= 3
2217240.20170483440110.6296364712216951.53029994439980.040191403
2216838.12367659439983.476755747
#Sta/Elev= 30
       0 2282.22     4.4 2280.83    22.3 2278.01    35.2 2273.92    43.9 2271.96
    71.5  2270.4    92.2 2268.28   118.6 2269.91   131.7 2268.12   166.9 2267.14
   171.2 2266.35   175.6 2263.64     180  2262.4   184.4  2262.1   188.8 2262.22
   194.6 2263.65   203.6 2266.33   218.8 2266.53   228.3 2267.63   245.9 2266.35
   270.1 2267.16   291.3 2264.22   311.7 2263.11   320.2 2266.82   328.2 2271.11
   340.2 2275.88   348.2 2277.94   356.2 2282.05   392.2  2289.3   430.3 2295.84
#Mann= 6 ,-1,0
       0      .1       0      80     .07       0     100     .06       0
   175.6    .045       0   194.6     .06       0     290      .1       0
#XS Ineff= 1 ,-1
  227.04430.2943 2269.69
Permanent Ineff=
       F
Bank Sta=175.6,194.6
XS Rating Curve= 0 ,0
Exp/Cntr(USF)=0,0
Exp/Cntr=0.3,0.1

Type RM Length L Ch R = 1 ,2369    ,112.2,112.2,112.2
XS GIS Cut Line= 4
2217254.81397304440001.3811833532217072.26031283439926.521049313
2217011.19020349439852.3175831152216951.43342982439844.437569005
#Sta/Elev= 30
       0  2270.9     7.2 2269.95    11.5 2268.28    32.8 2266.18    63.4 2264.32
    80.7 2265.21   121.7 2263.96   137.6 2264.03   141.2 2263.68     1472261.448
   149.8 2260.28   154.2 2259.34   158.5 2259.94   162.8 2261.36   167.7 2263.02
   171.5 2263.69   188.8  2264.1   203.7  2263.9   212.5 2264.56   215.4 2264.41
   228.9 2262.09   247.8 2262.55   250.8 2263.31   254.1 2264.81   272.2 2274.41
   286.4 2280.95   295.3 2283.77   304.5 2285.37   320.3 2288.83   353.7 2291.89
#Mann= 6 ,-1,0
       0     .05       0      90     .06       0     147    .045       0
   162.8     .06       0  197.31      .1       0  333.41     .05       0
#XS Ineff= 2 , 0
           82.93  2266.7
Permanent Ineff=
       F       F
Bank Sta=147,162.8
XS Rating Curve= 0 ,0
Exp/Cntr(USF)=0,0
Exp/Cntr=0.3,0.1

Type RM Length L Ch R = 1 ,2257    ,127,127,127
XS GIS Cut Line= 2
2217285.41892496439916.0611005062217016.59885777439759.794359935
#Sta/Elev= 30
       0 2272.93    29.2 2269.37    38.5 2267.84    47.7 2265.25      57 2263.88
    80.1 2262.34    89.3 2263.38   107.9 2262.32   126.4 2262.37   140.5 2261.39
     149  2258.5   154.1 2256.95   158.7 2257.21  162.69 2258.48   169.8 2260.82
   175.6 2261.65   210.8 2261.75   214.3 2262.63   218.9 2265.82   220.6 2266.55
   223.5 2267.36   228.3 2267.65   232.8 2268.43   236.6 2269.72   242.9 2273.94
   246.7 2276.07   255.9 2278.77   274.4 2282.92     279 2284.38   310.9 2286.83
#Mann= 7 ,-1,0
       0      .1       0      20     .05       0     130     .06       0
     149    .045       0  162.69     .06       0     250      .1       0
     280     .05       0
#XS Ineff= 2 , 0
           89.72 2265.39  174.73         2265.62
Permanent Ineff=
       F       F
Bank Sta=149,162.69
XS Rating Curve= 0 ,0
Exp/Cntr(USF)=0,0
Exp/Cntr=0.3,0.1

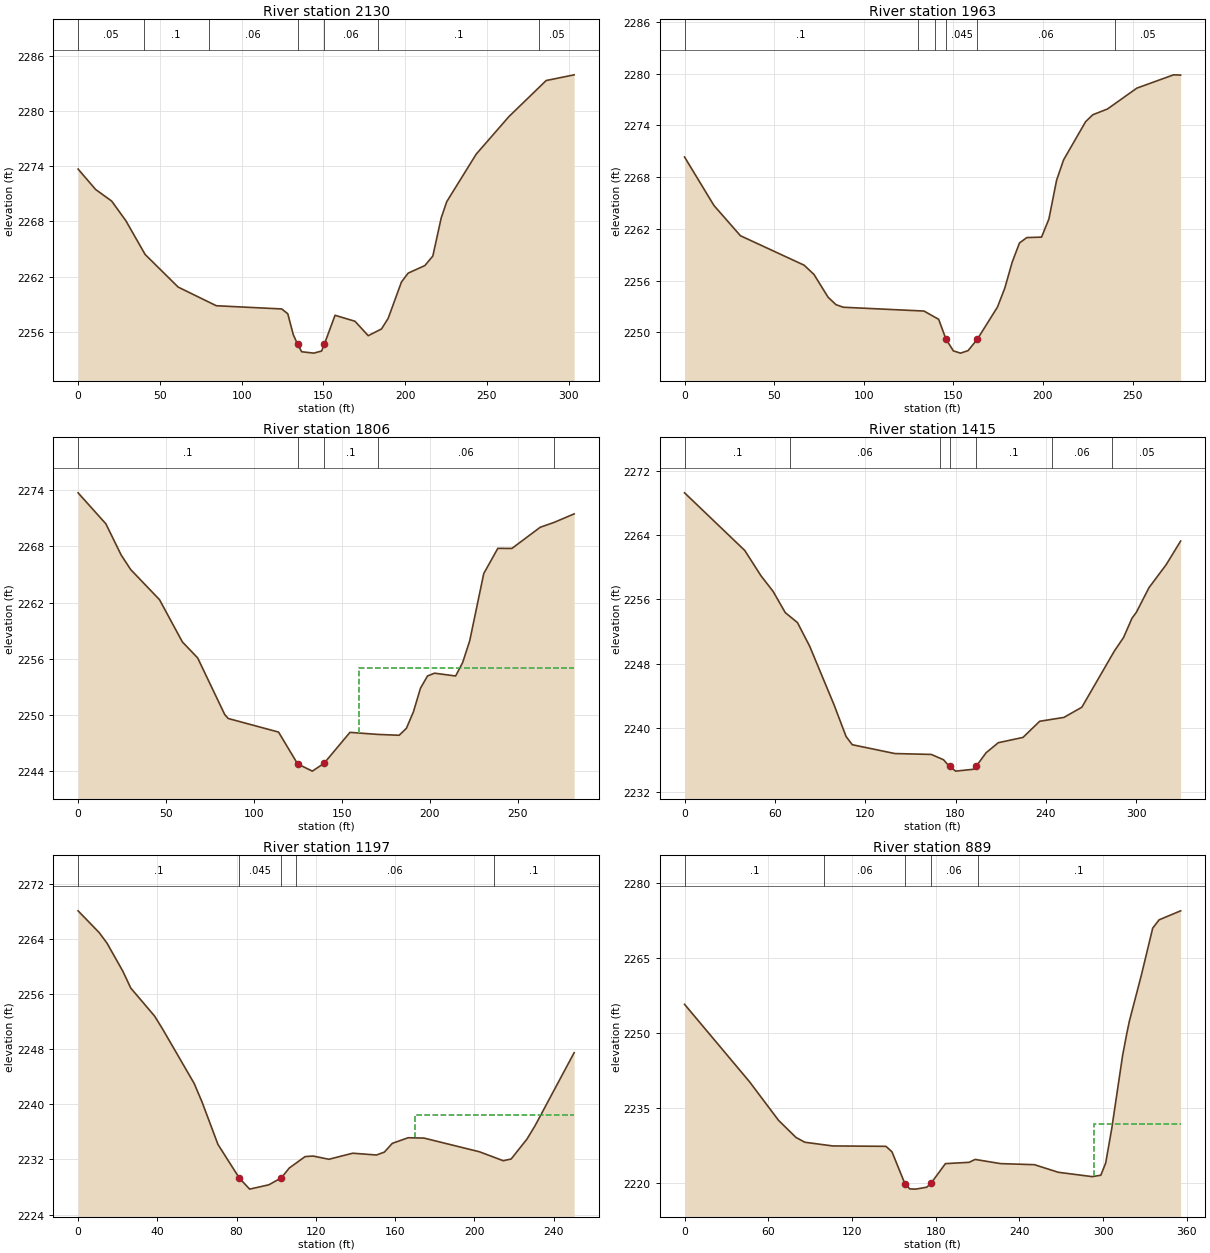
Type RM Length L Ch R = 1 ,2130    ,167.2,167.2,167.2
XS GIS Cut Line= 4
2217341.49412824439795.8441486632217242.99395187439739.370714211
2217156.31379667439723.6106859922217075.54365205439661.883908801
#Sta/Elev= 30
       0  2273.7    10.7 2271.48    20.5 2270.22    29.2 2268.08      41  2264.4
    61.2 2260.85    84.5 2258.82   124.5 2258.47   128.2 2257.95   131.6 2255.66
   134.2 2254.63   136.7 2253.81   144.1 2253.66   148.9 2253.89  150.54 2254.62
   157.1 2257.78   169.3 2257.13   177.4 2255.56   185.5 2256.29   189.6 2257.45
   197.7  2261.4   201.8 2262.37     212 2263.19   216.9 2264.23     222 2268.37
   225.4 2270.15   243.4 2275.32   263.4 2279.41   286.2 2283.34   303.3 2283.96
#Mann= 7 ,-1,0
       0     .05       0      40      .1       0      80     .06       0
   134.2    .045       0  150.54     .06       0  183.54      .1       0
  281.64     .05       0
Bank Sta=134.2,150.54
XS Rating Curve= 0 ,0
Exp/Cntr(USF)=0,0
Exp/Cntr=0.3,0.1

Type RM Length L Ch R = 1 ,1963    ,156.3,156.3,156.3
XS GIS Cut Line= 2
2217402.66040193439606.2365342052217132.38648006 439546.52485379
#Sta/Elev= 30
       0 2270.34    16.4 2264.72    31.2 2261.21    66.7  2257.8    72.2 2256.73
    80.1 2254.08    84.5 2253.22    88.6 2252.92   133.6 2252.48   141.8 2251.52
   145.9 2249.21     150 2247.86     154  2247.6   158.2 2247.89  163.312249.193
   174.6 2252.94   178.7 2255.14   182.8 2258.14   186.9 2260.38     191    2261
   199.2 2261.05   203.3 2263.15   207.6 2267.65   211.5 2270.01   223.8 2274.44
   227.8 2275.24     236 2275.91   252.4 2278.33   272.9 2279.87   276.8 2279.84
#Mann= 6 ,-1,0
       0      .1       0     130     .07       0     140     .06       0
   145.9    .045       0  163.31     .06       0     240     .05       0
Bank Sta=145.9,163.31
XS Rating Curve= 0 ,0
Exp/Cntr(USF)=0,0
Exp/Cntr=0.3,0.1

Type RM Length L Ch R = 1 ,1806    ,391.4,391.4,391.4
XS GIS Cut Line= 3
2217430.73084908439481.8663012982217292.24404006439422.856814145
2217160.84783271439415.931084985
#Sta/Elev= 30
       0 2273.73    15.8 2270.42    24.5 2267.09    29.9 2265.54    46.3 2262.32
    59.3 2257.81      68  2256.1    83.4 2250.05    85.4 2249.63     114 2248.18
124.84332244.782   133.2 2244.01139.83182244.833   154.6 2248.15   170.6 2247.93
   182.6 2247.84   186.7 2248.58   190.7 2250.34   194.7 2252.86   198.7 2254.17
   202.7 2254.47   214.7 2254.17   218.7 2255.61   222.7 2257.92   230.7 2265.11
   238.7  2267.8   246.7 2267.79   262.8 2270.05   270.8 2270.58   282.1 2271.48
#Mann= 5 ,-1,0
       0      .1       0124.8433    .045       0139.8318      .1       0
   170.6     .06       0   270.8     .05       0
#XS Ineff= 2 , 0
                             160            2255
Permanent Ineff=
       F       F
Bank Sta=124.8433,139.8318
XS Rating Curve= 0 ,0
Exp/Cntr(USF)=0,0
Exp/Cntr=0.3,0.1

Type RM Length L Ch R = 1 ,1415    ,218,218,218
XS GIS Cut Line= 3
2217438.40303867439042.0950762292217216.72723818439074.166189799
2217141.15797228439147.805792551
#Sta/Elev= 30
       0 2269.28      40  2262.1    50.8 2258.94    58.8 2257.01    66.9 2254.36
      75 2253.12    83.1 2250.18    99.3 2242.88   107.3 2238.93   111.4 2237.91
   139.7 2236.81   163.9  2236.7     172 2236.04     176  2235.2   180.1 2234.62
   191.8 2234.85  193.62  2235.2   200.3 2236.91   208.4 2238.16   224.8 2238.82
   235.9 2240.83     252 2241.31   263.9 2242.58   285.6 2249.61   291.6 2251.26
   297.2 2253.66   300.1  2254.4   308.5 2257.47   319.9 2260.33   329.5 2263.27
#Mann= 7 ,-1,0
       0      .1       0      70     .06       0     170      .1       0
     176    .045       0  193.62      .1       0  243.98     .06       0
  283.98     .05       0
Bank Sta=176,193.62
XS Rating Curve= 0 ,0
Exp/Cntr(USF)=0,0
Exp/Cntr=0.3,0.1

Type RM Length L Ch R = 1 ,1197    ,308.1,308.1,308.1
XS GIS Cut Line= 2
2217382.75650846438859.3167423482217132.38648006438858.269169007
#Sta/Elev= 30
       0 2268.14    10.6 2264.99    14.6 2263.44    22.6 2259.36    26.6 2256.91
    38.6 2252.85    42.6 2250.99    58.6 2243.05    62.6 2240.33    70.6 2234.19
    81.42229.294    86.6 2227.69    96.3 2228.32   102.6 2229.33   106.6 2230.76
   114.6 2232.42   118.6  2232.5   126.6 2232.03   138.6 2232.91   150.6 2232.65
   154.6 2233.07   158.6 2234.34   166.6 2235.16   174.6 2235.11   202.6 2233.12
   214.6 2231.82   218.6 2232.07   226.6 2234.97   230.6 2236.87   250.4 2247.52
#Mann= 5 ,-1,0
       0      .1       0    81.4    .045       0   102.6      .1       0
     110     .06       0     210      .1       0
#XS Ineff= 1 ,-1
  170.03250.3722  2238.5
Permanent Ineff=
       F
Bank Sta=81.4,102.6
XS Rating Curve= 0 ,0
Exp/Cntr(USF)=0,0
Exp/Cntr=0.3,0.1

Type RM Length L Ch R = 1 ,889     ,327.7,327.7,327.7
XS GIS Cut Line= 2
2217363.90018833438510.4748199242217029.72429268438631.993327435
#Sta/Elev= 30
       0 2255.77    46.5 2240.31    67.4 2232.56    79.9 2229.14    86.2 2228.19
   106.1 2227.45   144.4 2227.37   148.7 2226.27     158 2219.86   161.4 2218.86
   165.7 2218.81   173.6 2219.19   176.7 2219.99     187 2223.91     204 2224.17
   208.3 2224.75   226.6 2223.91   250.8  2223.7   267.9 2222.18   292.2 2221.31
   298.4 2221.59   301.9 2224.05   306.2 2230.86     314 2245.51   317.1 2250.05
   318.9 2252.44   327.4 2261.54   335.6 2271.01   340.2 2272.67   355.6 2274.47
#Mann= 5 ,-1,0
       0      .1       0     100     .06       0     158    .045       0
   176.7     .06       0     210      .1       0
#XS Ineff= 1 ,-1
   293.7355.5844 2231.88
Permanent Ineff=
       F
Bank Sta=158,176.7
XS Rating Curve= 0 ,0
Exp/Cntr(USF)=0,0
Exp/Cntr=0.3,0.1

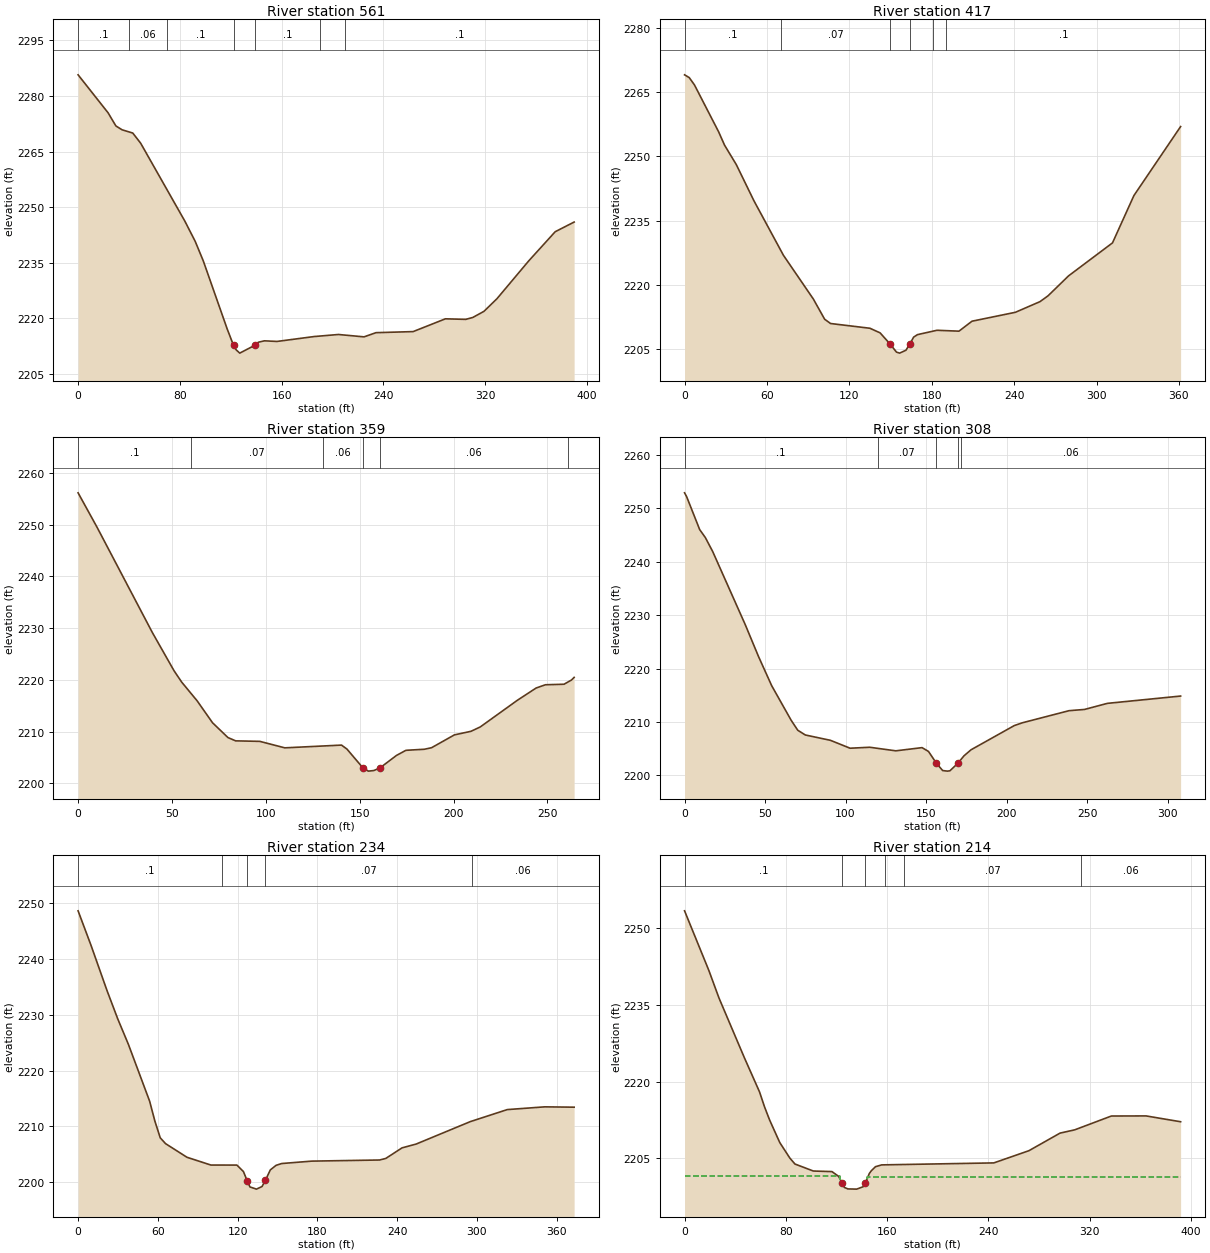
Type RM Length L Ch R = 1 ,561     ,143.9,143.9,143.9
XS GIS Cut Line= 3
2217224.57293403438184.6795109932217005.63010584438336.577645382
2216958.48930551438450.763139509
#Sta/Elev= 30
       0 2285.72    23.6 2275.46    29.7 2271.93    34.6 2270.88      43    2270
    49.2 2267.26      84 2246.19    92.1 2240.75    98.4 2235.52   117.3 2217.05
   122.2  2212.7   124.2 2211.51   127.1  2210.6  139.172212.754   141.7 2213.54
   146.5 2213.92   156.3 2213.75   185.5 2215.07   204.7 2215.63   224.8 2214.99
   234.2 2216.12   263.4 2216.41   288.8 2219.86   304.8 2219.71   310.4 2220.24
   319.1 2221.88   329.3 2225.28   354.1 2235.42   375.1 2243.37     390 2245.98
#Mann= 7 ,-1,0
       0      .1       0      40     .06       0      70      .1       0
   122.2    .045       0  139.17      .1       0     190     .08       0
     210      .1       0
Bank Sta=122.2,139.17
XS Rating Curve= 0 ,0
Exp/Cntr(USF)=0,0
Exp/Cntr=0.3,0.1

Type RM Length L Ch R = 1 ,417     ,58,58,58
XS GIS Cut Line= 4
 2217135.3050072438115.0368889942217022.83503756 438158.53942442
2216949.09293482  438239.70878932216889.67483766438356.422908735
#Sta/Elev= 30
       0 2269.04     3.4 2268.39     7.2 2266.69    24.8 2255.73    29.1 2252.62
    37.7 2248.05    50.5 2239.62      72 2226.87    93.8 2216.64     102 2211.93
   106.3 2210.93     135 2209.82   142.4 2208.74   149.8 2206.09   154.3 2204.25
   156.6 2204.01   161.2 2204.69     164 2206.11   166.8 2207.75   169.6 2208.33
   183.8 2209.35   199.8 2209.14   209.3 2211.47   240.9 2213.55   258.8 2216.04
   264.7 2217.41   279.6 2222.06   311.6 2229.77   327.2 2240.83   361.2 2256.95
#Mann= 6 ,-1,0
       0      .1       0      70     .07       0   149.8    .045       0
     164     .07       0  180.59     .08       0  190.59      .1       0
Bank Sta=149.8,164
XS Rating Curve= 0 ,0
Exp/Cntr(USF)=0,0
Exp/Cntr=0.3,0.1

Type RM Length L Ch R = 1 ,359     ,50.8,50.8,50.8
XS GIS Cut Line= 3
2217098.15447134438092.0939935332216999.74205075 438113.38178664
2216867.82752953438210.049306157
#Sta/Elev= 30
       0 2256.13    10.2 2249.41    39.6  2229.1    51.1 2221.75    55.2 2219.54
    63.4 2215.94    71.6  2211.7    79.8 2208.84    83.9  2208.2    96.8  2208.1
   110.1 2206.85   140.3 2207.38   143.2 2206.61   151.7 2202.98   154.6 2202.35
   157.5 2202.46  160.77 2202.97   169.6 2205.39   174.6 2206.37   184.5 2206.58
   188.3 2206.88   200.4 2209.35   209.3 2210.05   214.2 2210.89     234 2216.05
     244 2218.42   248.9 2219.04   258.8 2219.14   262.8 2219.96   264.2 2220.47
#Mann= 6 ,-1,0
       0      .1       0      60     .07       0  130.69     .06       0
   151.7    .045       0  160.77     .06       0  260.69      .1       0
Bank Sta=151.7,160.77
XS Rating Curve= 0 ,0
Exp/Cntr(USF)=0,0
Exp/Cntr=0.3,0.1

Type RM Length L Ch R = 1 ,308     ,74.7,74.7,74.7
BEGIN DESCRIPTION:
structure xs 4
END DESCRIPTION:
XS GIS Cut Line= 4
2217089.41422382438071.5104161372216939.72499679438097.819656115
2216897.22264213438117.969231026 2216806.6427537438178.705997899
#Sta/Elev= 30
       0  2252.9     1.3 2252.18     9.4 2246.01    12.9 2244.53    17.5 2241.89
    37.8 2228.14    45.9 2222.27    54.1 2216.79    66.2 2210.31    70.3 2208.44
      75 2207.55    90.6 2206.55   102.8 2205.07     115 2205.25   131.2 2204.58
   147.5 2205.18   151.5 2204.47156.44222202.249   160.3 2200.89   163.2 2200.78
   164.8 2200.84 169.6752202.228   173.6 2203.66     178 2204.79   204.8 2209.31
   209.9 2209.84   238.8  2212.1   248.4 2212.33   262.6 2213.47   308.1 2214.84
#Mann= 5 ,-1,0
       0      .1       0     120     .07       0156.4422    .045       0
 169.675     .07       0  171.98     .06       0
Bank Sta=156.4422,169.675
XS Rating Curve= 0 ,0
Exp/Cntr(USF)=0,0
Exp/Cntr=0.5,0.3

Type RM Length L Ch R = 1 ,234     ,19.8,19.8,19.8
BEGIN DESCRIPTION:
structure xs 3; 3.1 ft between structure and xs
END DESCRIPTION:
XS GIS Cut Line= 4
2217081.95835281438065.5753727852216993.52739652438061.959237026
2216930.17097597438017.2880581612216784.61521387438164.780814753
#Sta/Elev= 30
       0 2248.57     9.8 2242.35    21.8 2234.28    29.8 2229.26    37.8 2224.71
    53.8 2214.53    57.8 2210.93    61.8 2207.96    65.8 2206.92    81.9 2204.48
    99.9 2203.09   119.5 2203.08   124.4 2201.92 127.298 2200.22   129.3 2199.17
   134.2 2198.78   138.4 2199.25140.88732200.341   144.6 2202.21   148.9 2203.03
   153.2 2203.36   175.8 2203.79   226.8 2203.99   231.5 2204.27   243.7 2206.16
   254.3 2206.84   295.1 2210.86   322.9 2213.01   351.1  2213.5   373.2 2213.44
#Mann= 5 ,-1,0
       0      .1       0   108.5     .07       0 127.298    .045       0
140.8873     .07       0  296.03     .06       0
#XS Ineff= 2 ,-1
       0     124  2201.5     144   359.1  2201.3
Permanent Ineff=
       F       F
Bank Sta=127.298,140.8873
XS Rating Curve= 0 ,0
Exp/Cntr(USF)=0,0
Exp/Cntr=0.5,0.3

Type RM Length L Ch R = 1 ,214     ,18.7,18.7,18.7
BEGIN DESCRIPTION:
structure xs 2; 3.6 ft between structure and xs
END DESCRIPTION:
XS GIS Cut Line= 4
2217091.32743182438048.3165430252217002.89647553438044.700407266
2216942.07964685438001.3067781572216776.40615481438158.764034567
#Sta/Elev= 30
       0 2253.39    19.2 2241.72    27.2 2236.33    47.2 2224.68    59.2 2217.98
    63.2 2215.02    67.2 2212.46    75.2 2208.06    83.2 2205.01    87.2 2203.86
   101.7 2202.49   116.4 2202.38   121.7 2201.44  124.372200.164   126.2 2199.29
     129 2198.99   135.9 2198.95     141 2199.41   142.8 2200.14   145.9 2201.99
   147.5 2202.54   150.8 2203.34   155.7 2203.69   244.3 2204.08     272 2206.47
   296.6 2209.91   308.2 2210.55   337.1 2213.25   364.5 2213.27   391.8 2212.13
#Mann= 6 ,-1,0
       0      .1       0  124.37    .045       0   142.8     .07       0
   158.5      .1       0  173.22     .07       0  313.22     .06       0
#XS Ineff= 2 , 0
             123  2201.5     144          2201.3
Permanent Ineff=
       F       F
Bank Sta=124.37,142.8
XS Rating Curve= 0 ,0
Exp/Cntr(USF)=0,0
Exp/Cntr=0.5,0.3

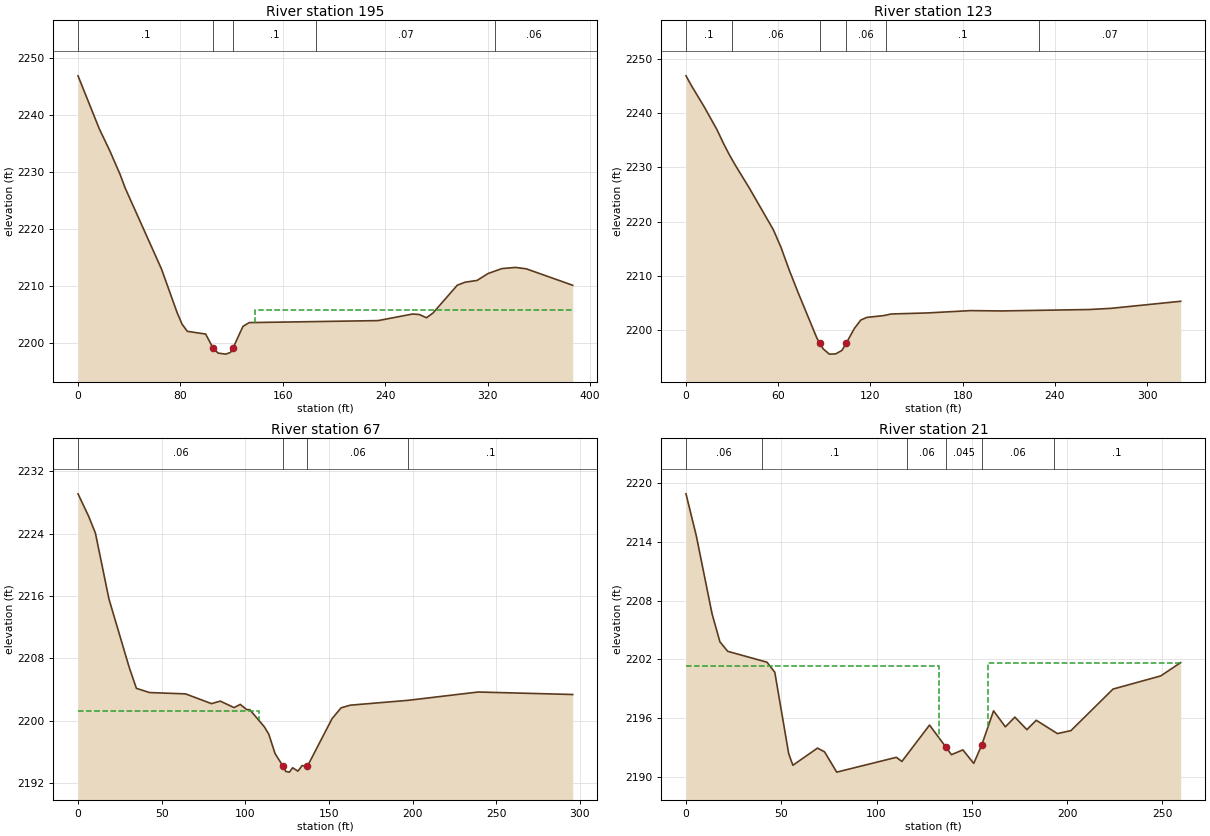
Type RM Length L Ch R = 1 ,195     ,71.8,71.8,71.8
BEGIN DESCRIPTION:
structure xs 1
END DESCRIPTION:
XS GIS Cut Line= 4
2217084.75263953 438030.235864232216998.95160015438018.401238109
2216950.29813721437984.8697974332216770.88116475438145.297885915
#Sta/Elev= 30
       0  2246.9    16.7 2237.56    24.8 2233.76    32.9 2229.58    36.9 2227.18
    65.2 2213.01    77.3 2205.42    81.3 2203.32    85.4 2202.08    99.7  2201.6
  105.372199.179   109.4 2198.26   115.4 2198.08   119.1 2198.38   121.1 2199.16
   128.8 2202.94   133.7 2203.61   234.4 2203.96   261.2 2205.11   266.6 2205.03
   272.2 2204.46   277.3  2205.3   296.2 2210.16   302.2 2210.69   311.7 2211.01
   320.2 2212.21     331 2213.08   341.7 2213.29   350.2 2213.04   386.4 2210.16
#Mann= 5 ,-1,0
       0      .1       0  105.37    .045       0   121.1      .1       0
   185.7     .07       0   325.7     .06       0
#XS Ineff= 2 , 0
                          137.98          2205.8
Permanent Ineff=
       F       F
Bank Sta=105.37,121.1
XS Rating Curve= 0 ,0
Exp/Cntr(USF)=0,0
Exp/Cntr=0.3,0.1

Type RM Length L Ch R = 1 ,123     ,56.7,56.7,56.7
BEGIN DESCRIPTION:
structure xs 4
END DESCRIPTION:
XS GIS Cut Line= 4
2217100.01717742437953.2020072332216980.48869591 437931.49289077
 2216941.1976653437973.0216131782216826.97009933438059.509301757
#Sta/Elev= 30
       0 2246.86     3.9 2244.88      12 2241.08    20.2 2236.92    24.2 2234.52
    28.3 2232.27    32.4 2230.25    41.2 2226.18    56.8 2218.52    61.8 2215.27
    67.3 2210.98      73 2206.88    85.2 2198.5186.986552197.619    89.3 2196.53
    93.3 2195.57    97.4 2195.61   101.5 2196.26104.38392197.648   109.6 2200.31
   113.7 2201.84   117.7 2202.34   128.6 2202.67   133.6 2202.97   156.9 2203.16
   185.2 2203.59   205.2 2203.53   262.3 2203.79   276.6 2204.01   321.9 2205.31
#Mann= 6 ,-1,0
       0      .1       0      30     .06       086.98655    .045       0
104.3839     .06       0  130.02      .1       0  230.02     .07       0
Bank Sta=86.98655,104.3839
XS Rating Curve= 0 ,0
Exp/Cntr(USF)=0,0
Exp/Cntr=0.5,0.3

Type RM Length L Ch R = 1 ,67      ,46,46,46
BEGIN DESCRIPTION:
structure xs 3; 14.2 ft between structure and xs
END DESCRIPTION:
XS GIS Cut Line= 5
2217106.39671561437803.8104586852217071.59388471 437809.49892073
2217035.35316048437882.9978207862216999.69853103437898.702415116
 2216894.8943012437996.381348927
#Sta/Elev= 30
       0 2229.12     6.3 2226.26    10.4 2224.08    18.5 2215.62    30.6 2206.86
    34.9 2204.16    42.8 2203.62    64.3 2203.45    79.8  2202.2    85.1 2202.52
    93.3 2201.69      97  2202.1   100.9 2201.43   102.7 2201.42   111.4 2199.23
   114.1 2198.26   117.8  2195.8122.57972194.165   124.3 2193.49   126.4 2193.41
   128.3 2193.97   131.5 2193.54     134 2194.25   137.2 2194.18   151.9 2200.27
   157.3 2201.66   162.8    2202   197.2 2202.62   239.3 2203.69   295.8 2203.37
#Mann= 4 ,-1,0
       0     .06       0122.5797    .045       0   137.2     .06       0
   197.2      .1       0
#XS Ineff= 2 ,-1
       0     108  2201.3     164     280  2201.6
Permanent Ineff=
       F       F
Bank Sta=122.5797,137.2
XS Rating Curve= 0 ,0
Exp/Cntr(USF)=0,0
Exp/Cntr=0.5,0.3

Type RM Length L Ch R = 1 ,21      ,,,
BEGIN DESCRIPTION:
structure xs 2; 10.2 ft between structure and xs
END DESCRIPTION:
XS GIS Cut Line= 5
2217109.47107135437749.5363440052217054.85650349 437762.56367212
2217023.79133644437821.6876997182216968.54387777437878.198925362
2216938.71254404437927.537040645
#Sta/Elev= 30
       0 2218.88     5.4 2214.61    13.7 2206.63    17.8 2203.79    21.9 2202.82
    42.5 2201.71    46.6 2200.69    53.9 2192.38    56.1  2191.2      69 2192.95
    72.7 2192.57    79.1  2190.5   110.4 2192.01   113.3 2191.59   127.8  2195.3
   136.4 2193.05   139.3 2192.28   145.3 2192.77     151 2191.39  155.182193.257
   161.4 2196.75   167.6 2195.12   172.6 2196.11   178.9 2194.83   183.8 2195.79
   194.9 2194.43     202 2194.73   224.1 2198.97   249.1 2200.31   259.6 2201.67
#Mann= 6 ,-1,0
       0     .06       0      40      .1       0  116.15     .06       0
   136.4    .045       0  155.18     .06       0  192.94      .1       0
#XS Ineff= 2 , 0
             133  2201.3   158.4          2201.6
Permanent Ineff=
       F       F
Bank Sta=136.4,155.18
XS Rating Curve= 0 ,0
Exp/Cntr(USF)=0,0
Exp/Cntr=0.5,0.3
LCMann Table=0

Chan Stop Cuts=-1
Use User Specified Reach Order=0
Composite Channel Slope=5